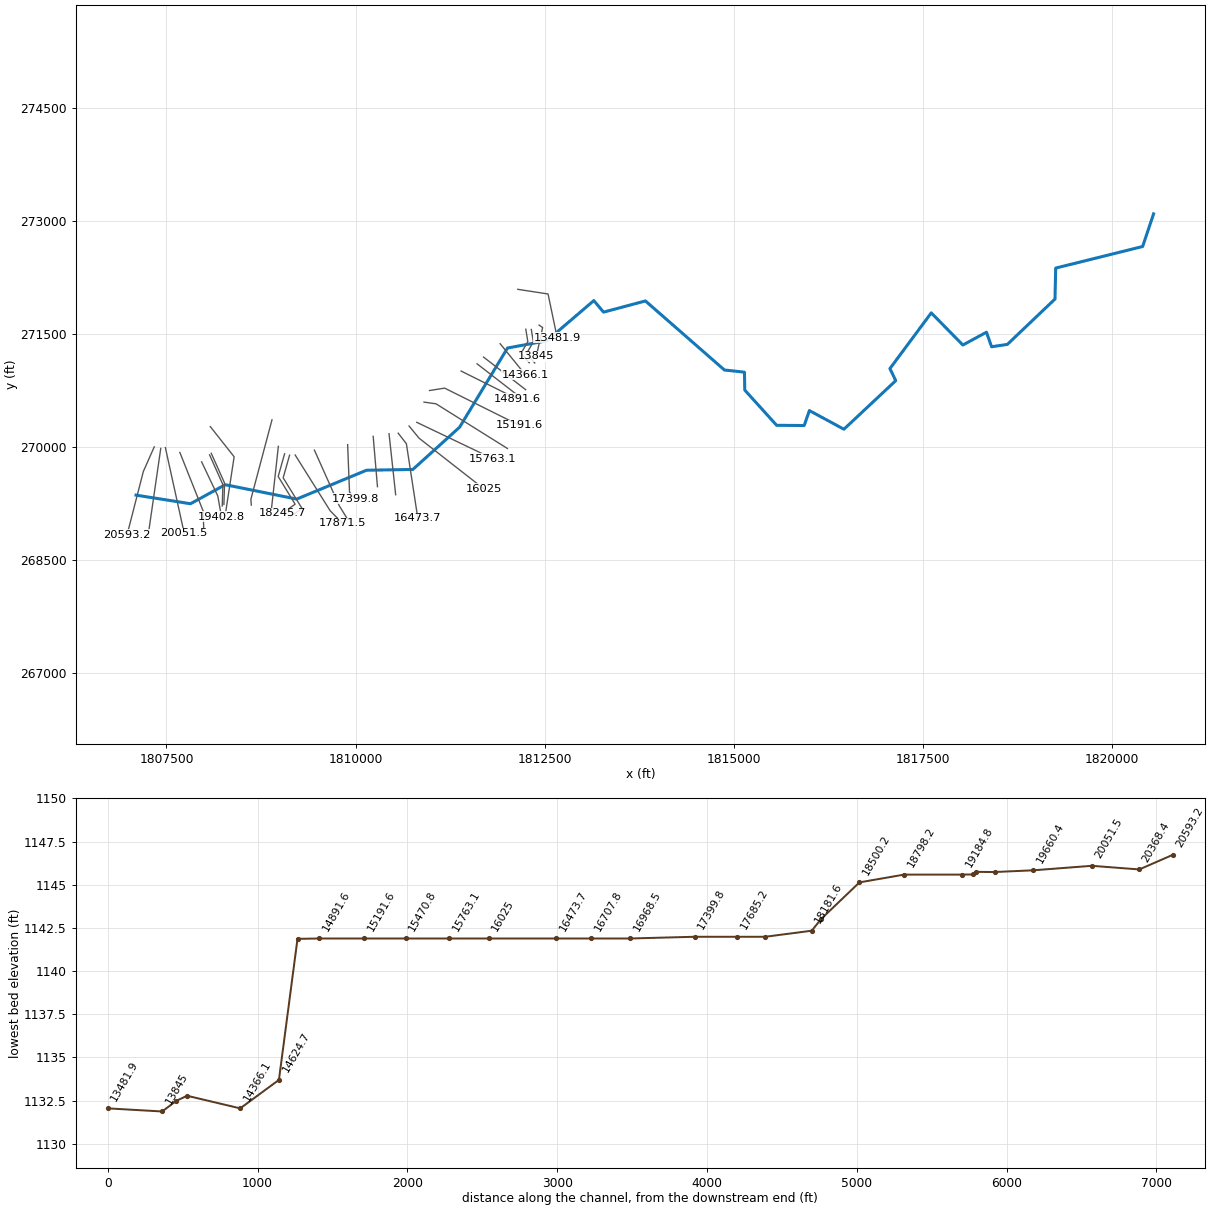
--- PLEASNTCK.prj (project) ---

Proj Title=PLEASNTCK
Current Plan=p01
Default Exp/Contr=0,0
English Units
Geom File=g01
Flow File=f01
Plan File=p01
BEGIN DESCRIPTION:
END DESCRIPTION:
DSS Export Rating Curves= 0
DSS Export Rating Curve Sorted= 0
DSS Export Volume Flow Curves= 0
DXF OffsetX= 0
DXF OffsetY= 0
DXF ScaleX= 0
DXF ScaleY= 0

--- PLEASNTCK.p01 (plan) ---

Plan Title=Floodplain
Program Version=4.00
Geom File=g01
Flow File=f01
K Sum by GR=0
Std Step Tol=0.01
Critical Tol=0.01
Num of Std Step Trials=20
Max Error Tol=0.3
Flow Tol Ratio=0.001
Split Flow NTrial=30
Split Flow Tol=0.02
Split Flow Ratio=0.02
Log Output Level=0
Friction Slope Method=1
Unsteady Friction Slope Method=2
Unsteady Bridges Friction Slope Method=1
Global Log Level=0
CheckData=False
Run HTab=0
Run UNet=0
Run PostProcess=0
UNET Theta=0
UNET Theta Warmup=0
UNET ZTol=0
UNET ZSATol=0
UNET MxIter=0
UNET MaxInSteps=0
UNET DtIC=0
UNET DtMin=0
UNET MaxCRTS=0
UNET WFStab=0
UNET SFStab=0
UNET WFX=0
UNET SFX=0
UNET DSS MLevel=0
UNET DZMax Abort=0
UNET Convert EG Bridges=0
UNET Use Existing IB Tables=0
UNET Froude Limit=0
UNET Froude Power=0
Write IC File=0
Echo Input=False
Echo Output=False
Write Detailed=0

--- PLEASNTCK.f01 (steady flow) ---

Flow Title=NFF Regression Equation
Program Version=4.10
Number of Profiles= 1
Profile Names=P100yr
River Rch & RM=PLEASNTCK,Main            ,20593.2
515.7828
River Rch & RM=PLEASNTCK,Main            ,19276.5
539.6554
River Rch & RM=PLEASNTCK,Main            ,17871.5
597.7703
River Rch & RM=PLEASNTCK,Main            ,17685.2
826.2153
River Rch & RM=PLEASNTCK,Main            ,16025
849.7181
River Rch & RM=PLEASNTCK,Main            ,15191.6
1057.365
River Rch & RM=PLEASNTCK,Main            ,12644.5
1174.784
River Rch & RM=PLEASNTCK,Main            ,7626
1284.014
River Rch & RM=PLEASNTCK,Main            ,7294.7
1461.526
River Rch & RM=PLEASNTCK,Main            ,4926
1560.156
River Rch & RM=PLEASNTCK,Main            ,211.1
1733.419
Boundary for River Rch & Prof#=PLEASNTCK,Main            , 1
Up Type= 0
Dn Type= 3
Dn Slope=0.01013
DSS Import GetInterval= 0
DSS Import GetPeak= 0
DSS Import FillOption= 0

--- PLEASNTCK.g01 (geometry) ---

Geom Title=USGS 10m DEM
Program Version=4.10

River Reach=PLEASNTCK       ,Main
Reach XY= 30
     1807097.096       269360.29      1807817.58      269246.037
     1808275.987      269498.812     1809221.923      269307.868
     1810144.202      269690.633     1810757.355      269700.988
     1811375.611       270261.91     1812009.242      271312.913
     1812528.739      271408.886     1813150.199       271942.42
      1813278.85      271788.897     1813832.588      271937.638
     1814876.983       271021.03     1815141.989        270992.4
     1815145.834      270754.754     1815567.484      270287.054
     1815931.665      270284.352     1816000.525      270482.635
     1816457.087      270234.983     1817142.496      270879.781
     1817065.179       271039.73     1817611.928      271779.392
     1818029.746      271352.676     1818341.768      271522.365
      1818409.57      271329.183     1818618.607       271361.24
     1819247.918       271963.01     1819257.098      272373.519
      1820406.64      272659.943     1820551.521      273093.017

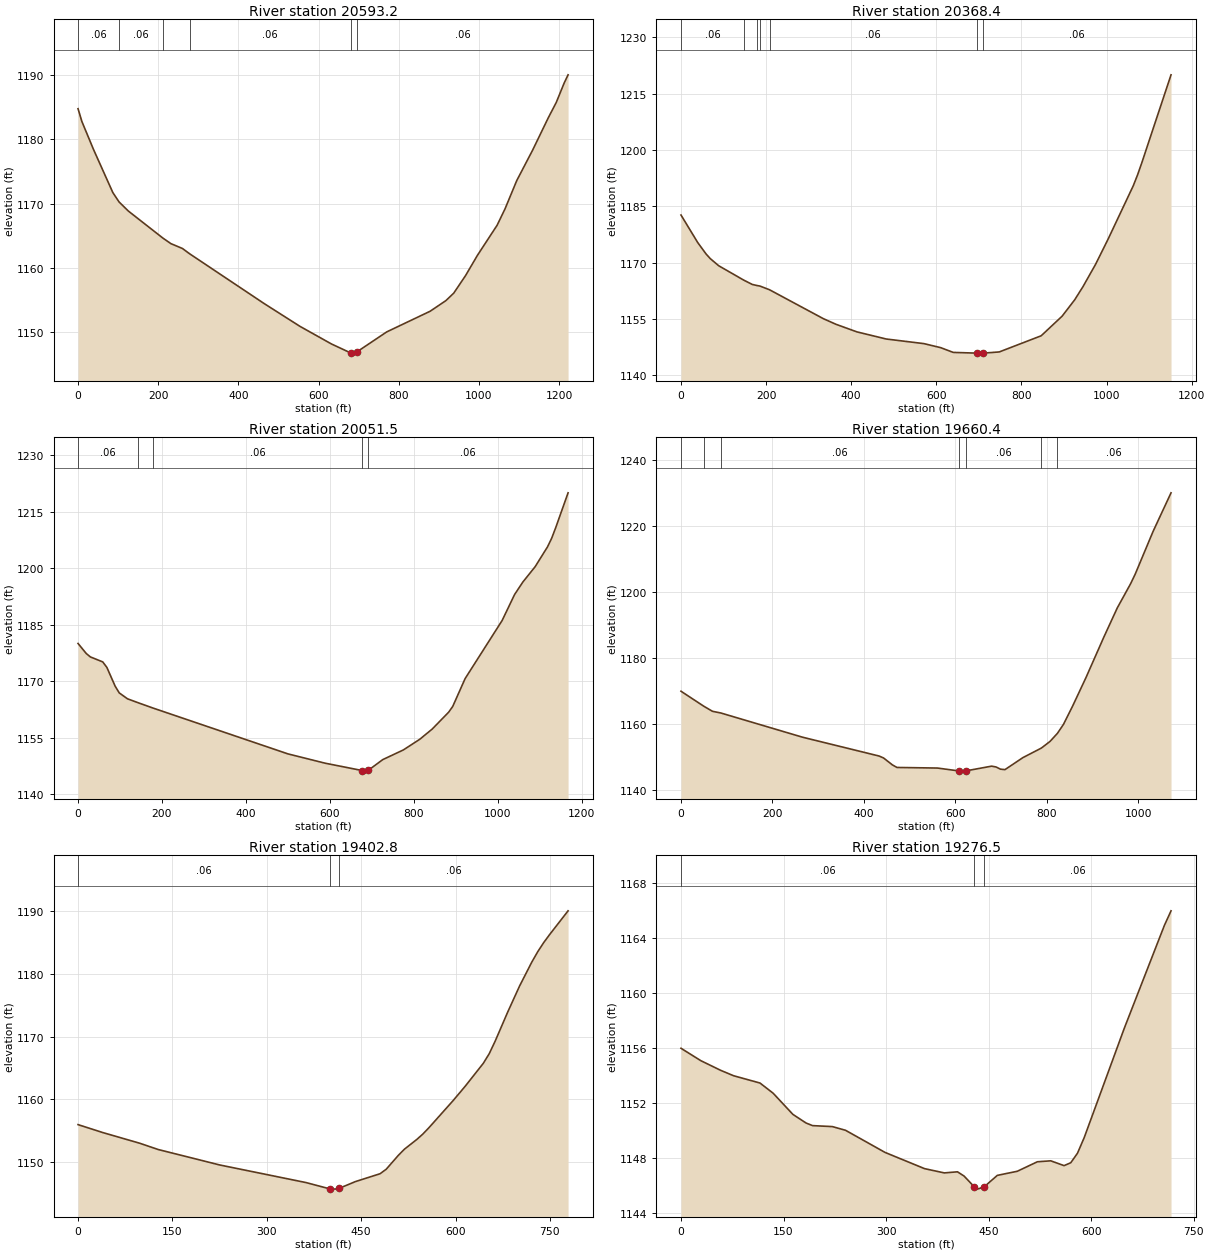
Type RM Length L Ch R = 1 ,20593.2 ,222.2,224.8,227
XS GIS Cut Line= 3
     1807338.241      270001.036     1807193.967      269674.511
     1806979.307      268836.171
#Sta/Elev= 30
       0 1184.75     9.6 1182.76    38.6 1178.41    86.8 1171.71   102.21170.261
   125.4 1168.84  212.09 1164.61   231.6 1163.77   260.5 1163.01  278.241162.195
   465.2 1154.41   553.7  1150.9   632.3 1148.16   680.8 1146.75   681.5 1146.74
   695.8 1146.94     770 1150.04   878.2 1153.25   917.5  1154.9   937.2 1156.07
   966.7  1158.8   996.2 1161.94  1045.4 1166.63    1065 1169.16  1094.5 1173.59
  1133.9  1178.3  1173.2 1183.36  1192.9 1185.72  1212.5 1188.72  1222.4 1190.02
#Mann= 6 ,-1 , 0
       0     .06       0   102.2     .06       0  212.09    .016       0
  278.24     .06       0   680.8    .045       0   695.8     .06       0
Bank Sta=680.8,695.8
XS Rating Curve= 0 ,0
Exp/Cntr=0.3,0.1

Type RM Length L Ch R = 1 ,20368.4 ,308.5,316.9,324.5
XS GIS Cut Line= 2
     1807423.975       269980.39     1807259.528      268840.801
#Sta/Elev= 30
       0 1182.67    39.4 1175.32      59 1172.28    68.9 1171.05    88.6 1169.16
  147.191165.346   167.3 1164.19  178.08  1163.9  185.361163.753  207.971162.767
   334.6 1155.06   364.1 1153.57   413.3 1151.55   482.2 1149.65   570.8 1148.42
   610.1 1147.35   639.7 1146.08   695.3 1145.89   710.3 1145.89   747.9 1146.21
   846.3 1150.51   895.5 1155.73     925 1160.08   944.7 1163.63   974.3 1169.58
  1003.8 1176.31  1062.8 1190.49  1072.7 1193.33  1082.5  1196.5  1151.4    1220
#Mann= 7 ,-1 , 0
       0     .06       0  147.19    .016       0  178.08     .06       0
  185.36     .08       0  207.97     .06       0   695.3    .045       0
   710.3     .06       0
Bank Sta=695.3,710.3
XS Rating Curve= 0 ,0
Exp/Cntr=0.3,0.1

Type RM Length L Ch R = 1 ,20051.5 ,386.8,391.1,392.7
XS GIS Cut Line= 2
     1807485.085      269991.555     1807734.918      268851.133
#Sta/Elev= 30
       0    1180    19.6 1177.33    29.4 1176.43    58.9  1175.1    68.7 1173.64
    88.3 1168.69    98.1 1166.88   117.7 1165.31  143.551164.246  177.571162.889
   500.3 1150.67   588.6 1148.21   676.91146.258   686.7  1146.1  691.231146.295
     726 1149.16     775 1151.72   814.3 1154.57   843.7 1157.26     883 1161.75
   892.8  1163.3   922.2 1170.67  1010.5 1186.12  1039.9 1192.96  1059.6 1196.29
    1089 1200.38  1118.4 1205.63  1128.2 1207.88    1138 1210.74  1167.5    1220
#Mann= 5 ,-1 , 0
       0     .06       0  143.55    .016       0  177.57     .06       0
   676.9    .045       0  691.23     .06       0
Bank Sta=676.9,691.23
XS Rating Curve= 0 ,0
Exp/Cntr=0.3,0.1

Type RM Length L Ch R = 1 ,19660.4 ,255.8,257.5,258.8
XS GIS Cut Line= 3
     1807676.841      269926.427     1807984.997      269148.868
     1807992.034      268913.858
#Sta/Elev= 30
       0    1170   50.181165.438    68.9 1163.93   87.191163.418   265.7  1156.1
     433 1150.41   442.8 1149.83   462.5  1147.7   472.3 1146.95   560.9 1146.77
   608.5 1145.88   619.9 1145.84   623.5 1145.93     679 1147.34   688.8  1147.1
   698.6 1146.43   708.5  1146.3   747.8 1149.94  787.921152.806   806.9 1154.82
   823.11157.268   836.4    1160     856 1165.42   885.4 1174.09   924.6 1186.37
     954  1195.2   983.3 1202.56   993.1 1205.39  1032.3 1218.34  1071.5    1230
#Mann= 7 ,-1 , 0
       0     .06       0   50.18    .016       0   87.19     .06       0
   608.5    .045       0   623.5     .06       0  787.92     .12       0
   823.1     .06       0
Bank Sta=608.5,623.5
XS Rating Curve= 0 ,0
Exp/Cntr=0.3,0.1

Type RM Length L Ch R = 1 ,19402.8 ,126.7,126.3,114.7
XS GIS Cut Line= 3
     1807964.619      269801.785     1808177.831       269349.88
     1808227.044      269075.057
#Sta/Elev= 30
       0    1156    39.2 1154.74      98 1153.04   127.4 1152.04   225.3 1149.58
   362.5 1146.78   400.2 1145.78   401.7 1145.74   411.5 1145.76   415.2 1145.87
   440.9 1146.94   480.1 1148.19   489.9 1148.91   509.3 1151.13   518.9  1152.1
   538.2 1153.62   547.8 1154.47   557.4 1155.47     596  1159.8   615.2 1162.08
   644.1 1165.74   653.7  1167.3   663.3 1169.34   682.6 1173.82   701.8 1178.04
   721.1 1181.82   730.7  1183.5   740.4 1184.98     750 1186.28   778.9    1190
#Mann= 3 ,-1 , 0
       0     .06       0   400.2    .045       0   415.2     .06       0
Bank Sta=400.2,415.2
XS Rating Curve= 0 ,0
Exp/Cntr=0.3,0.1

Type RM Length L Ch R = 1 ,19276.5 ,31.1,21.5,22.4
XS GIS Cut Line= 3
     1808069.563      269895.141     1808245.783      269499.158
     1808236.886      269215.759
#Sta/Elev= 30
       0    1156    28.9  1155.1    57.8  1154.4      77    1154   115.6 1153.47
   134.8 1152.73   163.7 1151.19     183 1150.56   192.6 1150.37   221.5  1150.3
   240.8 1150.03   298.6 1148.42   356.4 1147.24   385.3 1146.93   404.5 1147.01
   414.2  1146.7  429.341145.907   433.4 1145.75   443.2  1145.9   462.8 1146.75
   492.1 1147.05   521.4 1147.74     541 1147.81   560.5 1147.46   570.3 1147.67
   580.1 1148.36   589.9 1149.49   648.5 1157.44   707.2 1164.93     717    1166
#Mann= 3 ,-1 , 0
       0     .06       0  429.34    .045       0   443.2     .06       0
Bank Sta=429.34,443.2
XS Rating Curve= 0 ,0
Exp/Cntr=0.3,0.1

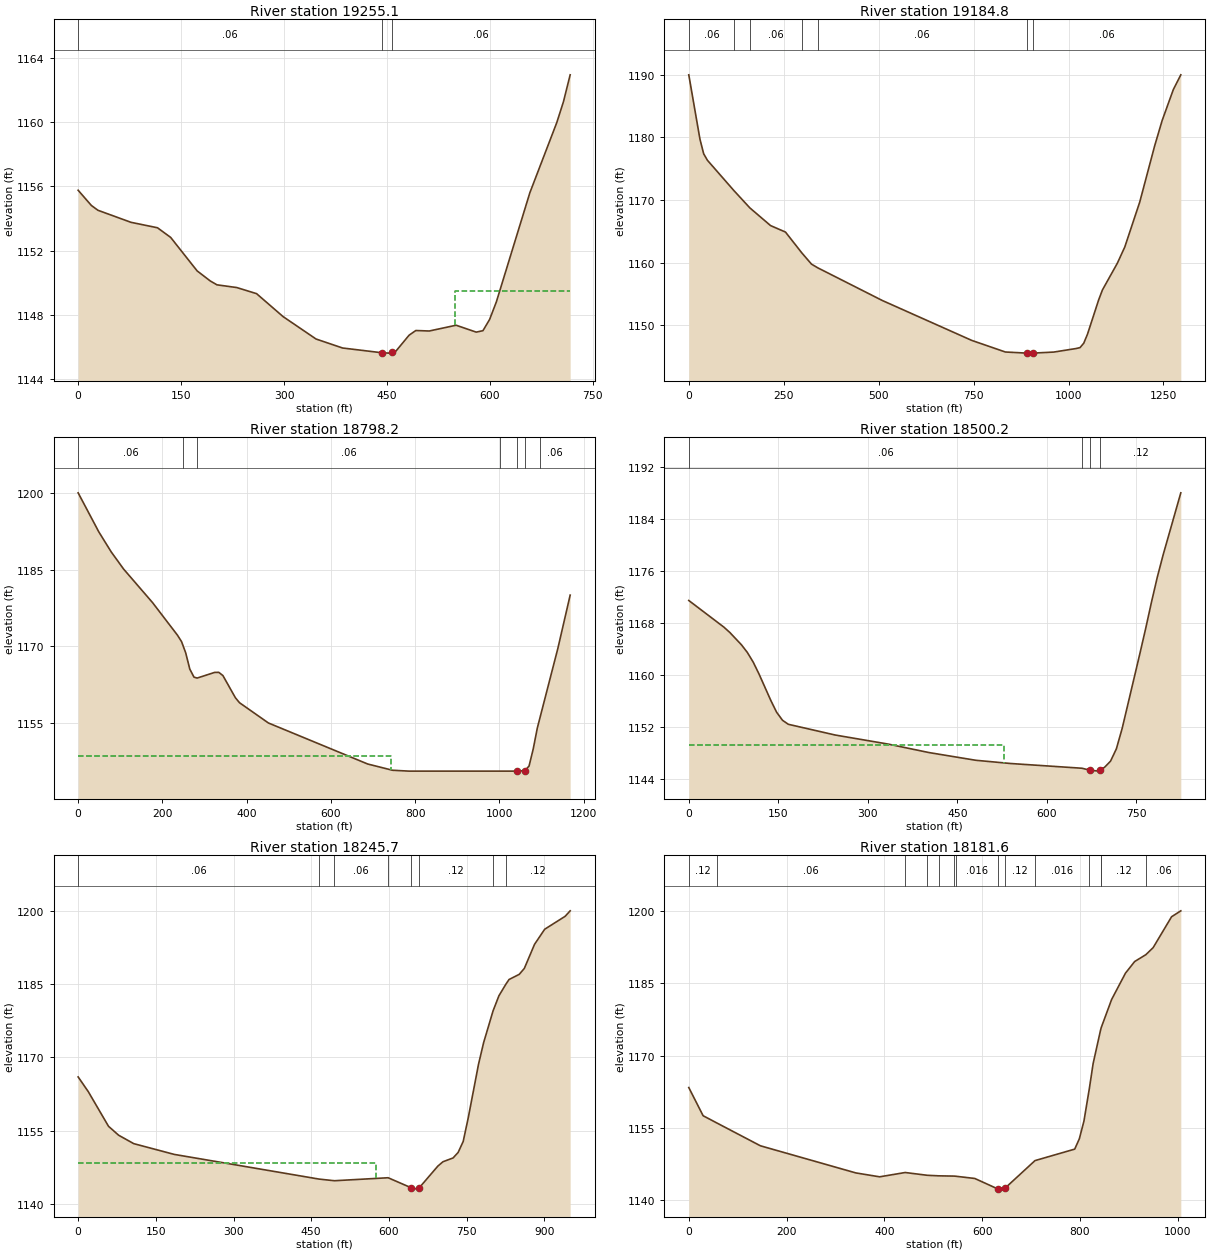
Type RM Length L Ch R = 1 ,19255.1 ,73.6,70.3,67.5
XS GIS Cut Line= 3
     1808091.699      269915.974     1808267.918      269519.992
     1808259.021      269236.593
#Sta/Elev= 30
       0 1155.76    19.3 1154.81    28.9 1154.51      77 1153.76   115.6 1153.42
   134.8 1152.82   173.4 1150.73   192.6  1150.1   202.3 1149.86   231.2 1149.69
     260 1149.31   298.6 1147.88   346.7 1146.48   385.3 1145.92   443.2 1145.62
     453  1145.6  457.691145.652   462.8 1145.71   482.3 1146.72   492.1 1147.01
   511.6 1146.98   550.8 1147.34   580.1 1146.91   589.9    1147   599.6  1147.7
   609.4 1148.79   658.3 1155.61   697.4 1159.97   707.2 1161.28     717 1162.96
#Mann= 3 ,-1 , 0
       0     .06       0   443.2    .045       0  457.69     .06       0
#XS Ineff= 2 , 0
                          549.85         1149.47
Permanent Ineff=
       F       F
Bank Sta=443.2,457.69
XS Rating Curve= 0 ,0
Exp/Cntr=0.3,0.1

Type RM Length L Ch R = 1 ,19184.8 ,385.5,386.5,382.6
XS GIS Cut Line= 3
     1808079.406      270269.538     1808394.366       269869.38
     1808276.256      269091.978
#Sta/Elev= 30
       0    1190    29.4 1179.73    39.2  1177.4      49 1176.37     1191171.516
   160.91168.761   215.4 1165.94   254.6 1164.91  297.921161.565   323.2 1159.79
  339.091159.219   509.2    1154   745.1 1147.62   833.6 1145.77   890.2 1145.59
   905.2 1145.59   961.4 1145.76  1020.4 1146.33  1030.2 1146.47    1040 1147.17
  1049.8  1148.6  1079.3 1154.09  1089.2 1155.67  1128.5 1159.94  1148.1 1162.53
  1187.4 1169.69  1226.8 1178.68  1246.4  1182.7  1275.9 1187.65  1295.6    1190
#Mann= 7 ,-1 , 0
       0     .06       0     119     .12       0   160.9     .06       0
  297.92    .016       0  339.09     .06       0   890.2    .045       0
   905.2     .06       0
Bank Sta=890.2,905.2
XS Rating Curve= 0 ,0
Exp/Cntr=0.3,0.1

Type RM Length L Ch R = 1 ,18798.2 ,295,298,300.9
XS GIS Cut Line= 3
     1808894.786      270359.498     1808615.837      269305.808
     1808621.076      269227.939
#Sta/Elev= 30
       0    1200    49.1 1192.36    78.6 1188.44     108 1185.09   176.8 1178.52
   235.7 1172.18   245.5 1170.91  249.151170.094   255.3 1168.72   265.1 1165.53
     275 1163.97  282.551163.785     324 1164.89   333.9  1164.9   343.7 1164.27
   373.2 1159.95     383 1158.97   451.7    1155   687.4 1146.98   746.3 1145.76
   785.6 1145.59  1001.6 1145.59  1040.9 1145.59  1060.5 1145.69  1070.4 1146.58
  1080.2 1149.89    1090    1154 1095.851155.876  1138.8 1169.59    1168    1180
#Mann= 7 ,-1 , 0
       0     .06       0  249.15    .016       0  282.55     .06       0
  1001.6     .12       0  1040.9    .045       0  1060.5     .12       0
 1095.85     .06       0
#XS Ineff= 2 , 0
          743.47 1148.62
Permanent Ineff=
       F       F
Bank Sta=1040.9,1060.5
XS Rating Curve= 0 ,0
Exp/Cntr=0.3,0.1

Type RM Length L Ch R = 1 ,18500.2 ,240.2,254.6,270.1
XS GIS Cut Line= 2
     1808979.033      270007.989     1808889.138      269188.319
#Sta/Elev= 30
       0 1171.42    58.9 1167.31    68.7  1166.5    88.4 1164.58    98.2 1163.41
     108 1161.92   117.8 1160.08   137.4 1156.04   147.2 1154.21   157.1 1152.97
   166.9 1152.35   245.4  1150.7   333.8 1149.31   402.5    1148     481 1146.81
   539.9 1146.31  658.921145.584  672.931145.273   687.2 1145.14   689.31145.272
     697 1145.75   706.8 1146.67   716.6 1148.57   726.4 1151.75   755.9  1163.2
   765.7  1167.1   775.5 1171.19   785.3 1175.05   795.1 1178.49   824.6    1188
#Mann= 4 ,-1 , 0
       0     .06       0  658.92     .12       0  672.93    .045       0
   689.3     .12       0
#XS Ineff= 2 , 0
          528.38 1149.12
Permanent Ineff=
       F       F
Bank Sta=672.93,689.3
XS Rating Curve= 0 ,0
Exp/Cntr=0.3,0.1

Type RM Length L Ch R = 1 ,18245.7 ,51.2,64,67.5
XS GIS Cut Line= 4
     1809061.441      269908.958     1808976.823      269608.193
     1809200.639      269239.754     1809032.907       269119.34
#Sta/Elev= 30
       0    1166    19.5    1163    58.6  1155.9    78.1 1154.07   107.4 1152.34
   185.5 1150.14  465.061145.087  494.671144.748  598.521145.359  643.011143.312
   655.4 1143.03  658.131143.246   694.6 1147.75   704.3 1148.63   723.9 1149.41
   733.7 1150.54   743.5  1152.8   753.4 1157.73     773 1168.57   782.9 1173.02
   801.11179.509   812.4  1182.6  825.891184.986     832 1185.94   851.7    1187
   861.5 1188.21   881.2 1193.14   900.8 1196.23   940.2 1198.87     950    1200
#Mann= 8 ,-1 , 0
       0     .06       0  465.06     .12       0  494.67     .06       0
  598.52     .12       0  643.01    .045       0  658.13     .12       0
   801.1     .06       0  825.89     .12       0
#XS Ineff= 2 , 0
          575.98 1148.29
Permanent Ineff=
       F       F
Bank Sta=643.01,658.13
XS Rating Curve= 0 ,0
Exp/Cntr=0.3,0.1

Type RM Length L Ch R = 1 ,18181.6 ,320.8,310.2,306.5
XS GIS Cut Line= 4
     1809127.414      269890.729     1809042.796      269589.964
     1809292.077      269183.444     1809114.798      269058.357
#Sta/Elev= 30
       0 1163.39    29.3 1157.55   58.261156.003   146.5 1151.32   341.6  1145.7
   390.3 1144.89  442.651145.783  487.751145.208  511.231145.094  542.77 1145.04
  546.241145.008   584.9 1144.55   631.6  1142.4   633.6 1142.34   646.6 1142.52
  708.041148.249   789.3 1150.63   798.7 1152.75   808.2 1156.45  819.371163.266
     827 1168.38  842.211175.307  843.491175.797   864.8 1181.64   893.1 1187.09
   911.9  1189.5  934.771190.922   949.7 1192.38   987.4 1198.78  1006.3 1200.01
#Mann= 14 ,-1 , 0
       0     .12       0   58.26     .06       0  442.65    .016       0
  487.75     .12       0  511.23    .016       0  542.77     .12       0
  546.24    .016       0   631.6    .045       0   646.6     .12       0
  708.04    .016       0  819.37     .12       0  842.21     .06       0
  843.49     .12       0  934.77     .06       0
Bank Sta=631.6,646.6
XS Rating Curve= 0 ,0
Exp/Cntr=0.3,0.1

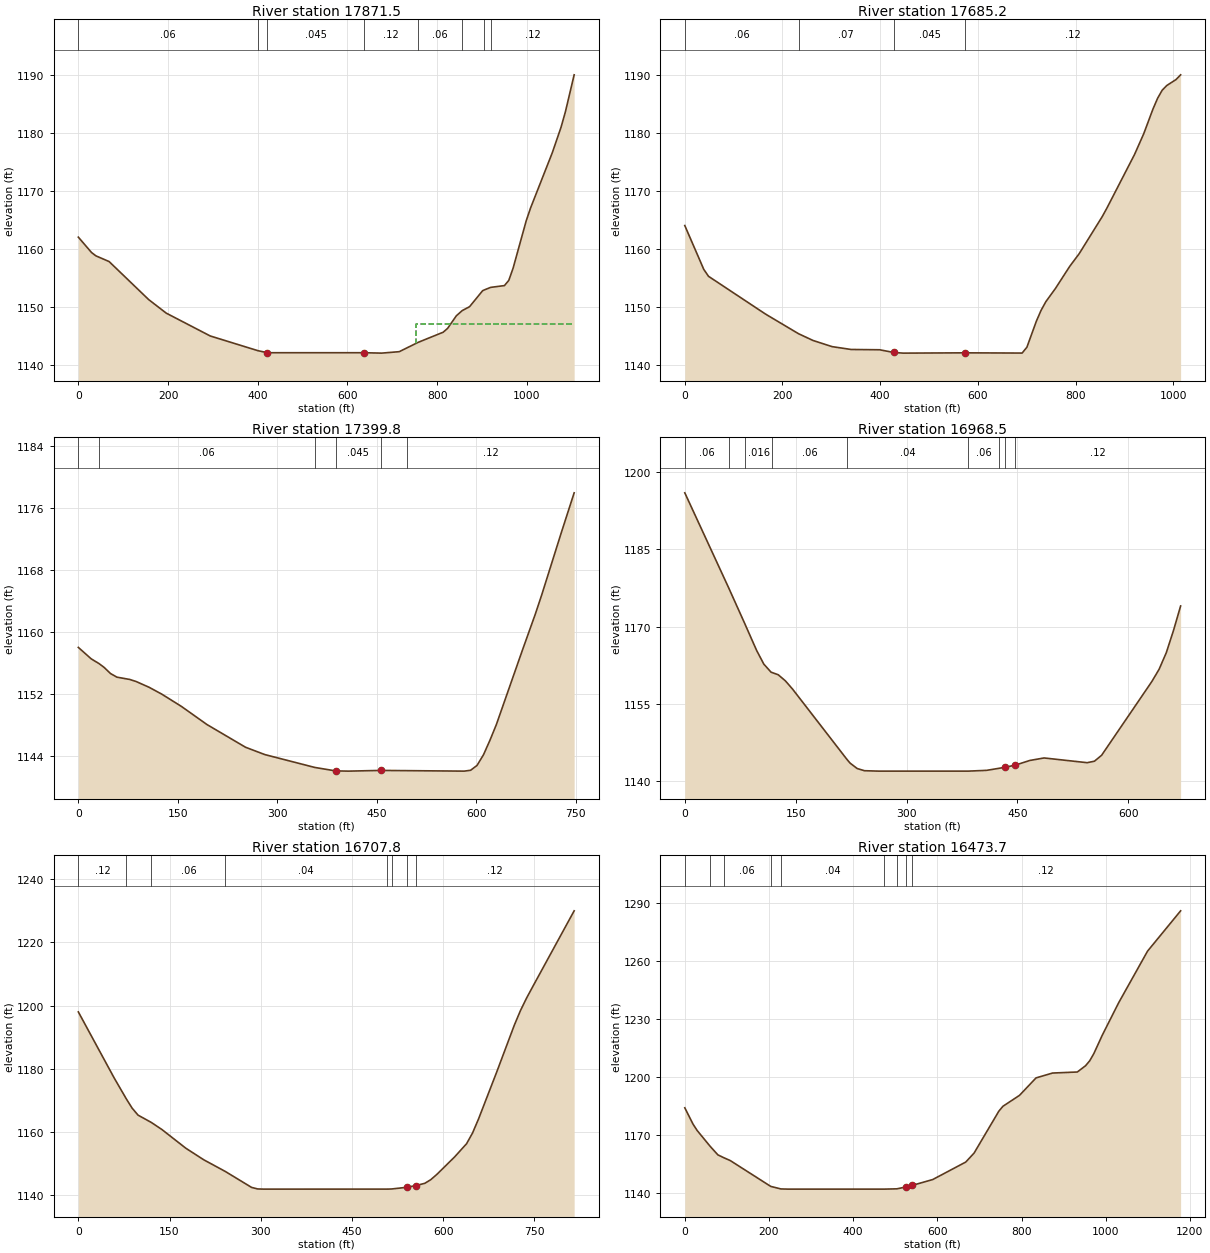
Type RM Length L Ch R = 1 ,17871.5 ,189.5,186.3,183.2
XS GIS Cut Line= 3
     1809201.453      269892.696     1809664.051       269153.07
     1809827.648      268986.921
#Sta/Elev= 30
       0    1162    29.4 1159.35    39.2 1158.77    68.6 1157.79   156.8 1151.23
     196 1148.89   294.1 1144.95  400.351142.414   421.5 1142.06   637.1 1142.06
   676.3 1141.99   715.6 1142.24  757.661143.846   813.6  1145.6   823.4 1146.26
     843 1148.44  855.981149.329   872.4    1150   901.5 1152.76  905.151152.888
  919.311153.332   950.1 1153.64   959.8 1154.53   969.5 1156.66   998.7 1164.82
  1008.4 1167.03    1057 1176.59  1076.4 1180.97  1086.1 1183.63  1105.6    1190
#Mann= 8 ,-1 , 0
       0     .06       0  400.35     .04       0   421.5    .045       0
   637.1     .12       0  757.66     .06       0  855.98     .04       0
  905.15     .06       0  919.31     .12       0
#XS Ineff= 2 , 0
                          752.29         1146.94
Permanent Ineff=
       F       F
Bank Sta=421.5,637.1
XS Rating Curve= 0 ,0
Exp/Cntr=0.3,0.1

Type RM Length L Ch R = 1 ,17685.2 ,294,285.4,276.8
XS GIS Cut Line= 3
      1809455.78      269957.533     1809784.031      269219.892
     1809892.762      269042.933
#Sta/Elev= 30
       0    1164    38.9 1156.43    48.6 1155.24   165.4 1148.72  232.911145.336
   262.6 1144.17   301.6 1143.11   340.5 1142.62   398.8 1142.57     428  1142.1
   447.5 1141.99   573.9 1142.04   690.6    1142   700.4 1143.01   719.8 1147.51
   729.6  1149.4   739.3 1150.88   758.7 1153.13   787.9 1156.94   807.4 1159.14
   854.6 1165.54     864 1166.98   920.7 1176.25   939.6 1179.84   958.4 1184.08
   967.9 1185.94   977.3 1187.34   986.8 1188.16  1005.6 1189.18  1015.1    1190
#Mann= 4 ,-1 , 0
       0     .06       0  232.91     .07       0     428    .045       0
   573.9     .12       0
Bank Sta=428,573.9
XS Rating Curve= 0 ,0
Exp/Cntr=0.3,0.1

Type RM Length L Ch R = 1 ,17399.8 ,429.3,431.2,432.9
XS GIS Cut Line= 3
     1809895.114       270030.01     1809919.957      269400.001
     1809998.697      269312.949
#Sta/Elev= 30
       0    1158    19.4 1156.52   31.191155.906    38.8 1155.42    48.5 1154.62
    58.2 1154.15    77.6 1153.85    87.3 1153.58   106.7 1152.84   126.1 1151.94
   155.2 1150.38     194 1148.02   252.2 1145.08   281.3 1144.13  356.591142.468
     388 1142.02   407.4 1141.99   455.9 1142.08  496.381142.051     582 1141.99
   591.7  1142.1   601.4 1142.73   611.1  1144.1   620.8 1145.97   630.5    1148
   669.6 1157.58   689.2 1162.28     699  1164.8   728.3 1172.79   747.9    1178
#Mann= 6 ,-1 , 0
       0    .016       0   31.19     .06       0  356.59     .04       0
     388    .045       0   455.9     .06       0  496.38     .12       0
Bank Sta=388,455.9
XS Rating Curve= 0 ,0
Exp/Cntr=0.3,0.1

Type RM Length L Ch R = 1 ,16968.5 ,261,260.8,260.4
XS GIS Cut Line= 2
     1810232.703      270140.747     1810289.447      269472.315
#Sta/Elev= 30
       0    1196   59.16 1177.59   81.091170.588    97.2 1165.35   106.9  1162.7
   116.7 1161.13  118.541161.035   126.4 1160.63   136.1 1159.44   145.8 1157.84
  219.141144.213   223.6 1143.45   233.3 1142.39   243.1 1141.97   262.5 1141.89
  383.27 1141.89   408.3 1142.04  424.741142.431   433.7 1142.65   447.2 1143.06
   466.7 1143.96   486.1 1144.45   544.4 1143.53   554.2 1143.82   563.9 1144.97
     632 1159.34   641.7  1161.7   651.4 1164.91   661.1 1169.21   670.8    1174
#Mann= 9 ,-1 , 0
       0     .06       0   59.16     .12       0   81.09    .016       0
  118.54     .06       0  219.14     .04       0  383.27     .06       0
  424.74     .12       0   433.7    .045       0   447.2     .12       0
Bank Sta=433.7,447.2
XS Rating Curve= 0 ,0
Exp/Cntr=0.3,0.1

Type RM Length L Ch R = 1 ,16707.8 ,233,234,235
XS GIS Cut Line= 2
     1810442.396      270176.135     1810530.193       269365.38
#Sta/Elev= 30
       0    1198      59 1177.07   79.12  1170.4    88.4 1167.55    98.2 1165.32
  120.031163.002   137.6 1160.74   176.8 1154.84   206.3 1151.18  241.771147.479
   284.9 1142.44   294.8 1141.95   304.6 1141.89  508.131141.897  515.221141.935
   539.9 1142.46   554.9    1143   569.9 1143.73   579.7 1144.89   589.5 1146.52
     619 1152.11   638.6 1156.28   648.5 1159.71   658.3 1164.14   687.8  1178.8
   717.2 1193.86   727.1 1198.38   736.9 1202.25   746.7 1205.76   815.5    1230
#Mann= 8 ,-1 , 0
       0     .12       0   79.12    .016       0  120.03     .06       0
  241.77     .04       0  508.13     .06       0  515.22     .12       0
   539.9    .045       0   554.9     .12       0
Bank Sta=539.9,554.9
XS Rating Curve= 0 ,0
Exp/Cntr=0.3,0.1

Type RM Length L Ch R = 1 ,16473.7 ,431.6,448.7,464.8
XS GIS Cut Line= 3
     1810563.684      270182.332     1810671.897      270042.521
     1810823.027      269052.884
#Sta/Elev= 30
       0    1184    19.6 1175.53    29.5 1172.22   60.021164.117    78.6 1159.63
   92.181158.207     108 1156.68   204.2  1143.3  228.281141.988   245.5 1141.89
  473.82 1141.89  503.781142.045     525 1142.99     540 1143.81     589 1146.85
   667.5 1155.92   687.2 1160.55   746.1 1182.27   755.9 1184.81   795.1 1190.44
   834.4 1199.48   873.6    1202   932.5 1202.54   952.2 1205.82     962 1208.37
   971.8 1212.09   991.4 1221.43  1030.7  1238.4  1099.4 1265.14  1177.9    1286
#Mann= 9 ,-1 , 0
       0     .12       0   60.02    .016       0   92.18     .06       0
   204.2     .12       0  228.28     .04       0  473.82     .06       0
  503.78     .12       0     525    .045       0     540     .12       0
Bank Sta=525,540
XS Rating Curve= 0 ,0
Exp/Cntr=0.3,0.1

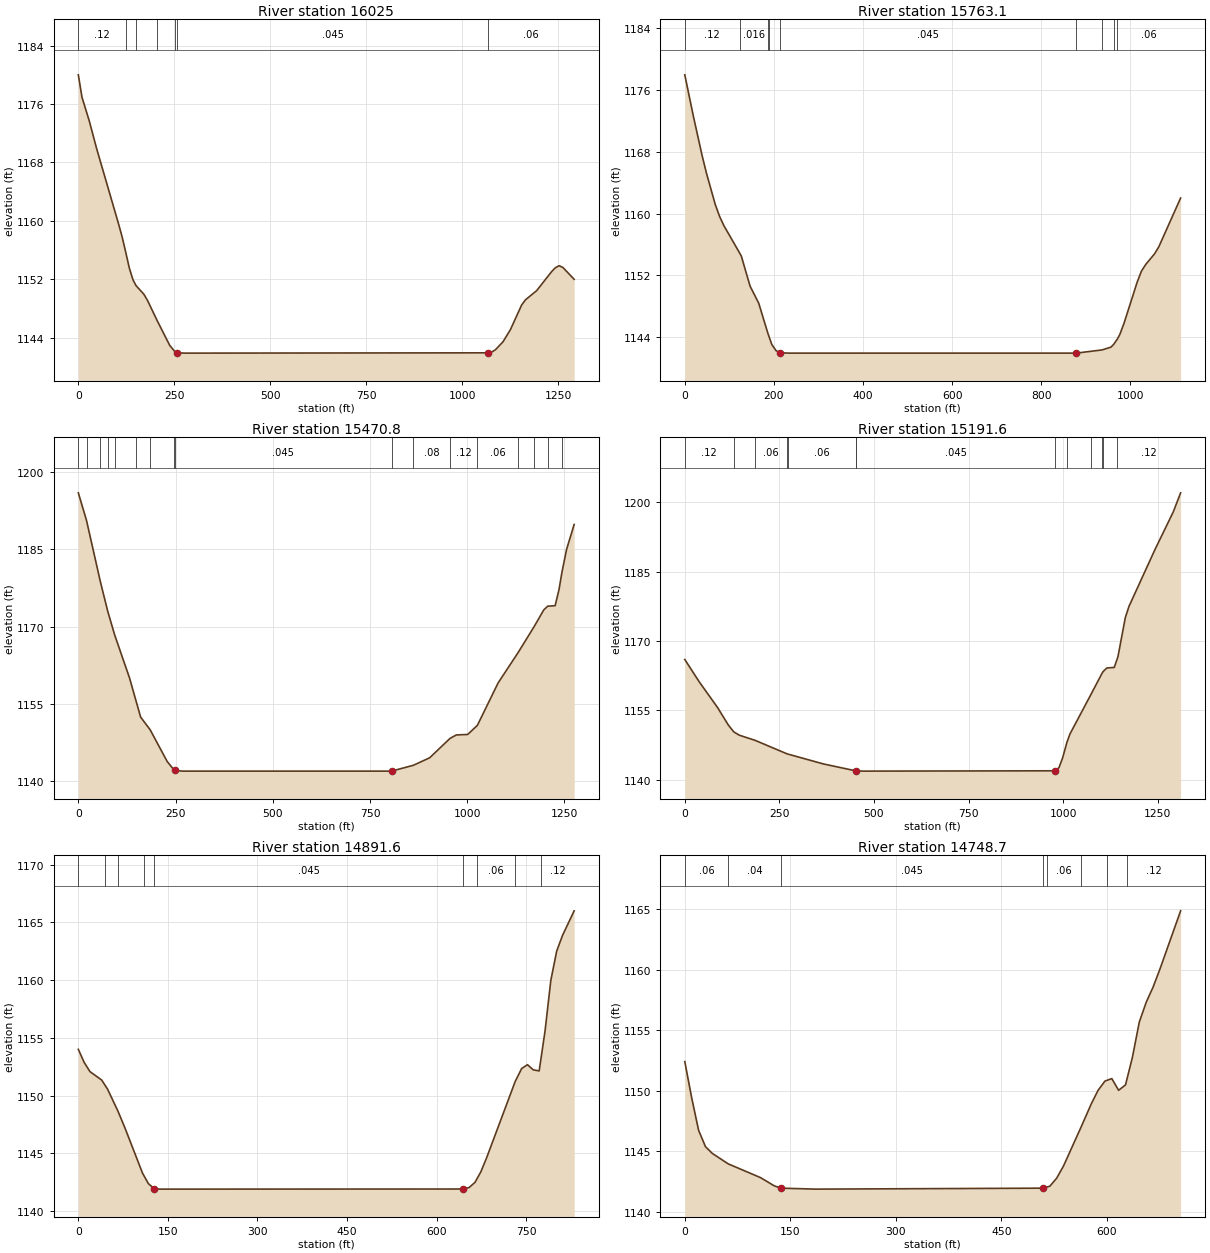
Type RM Length L Ch R = 1 ,16025   ,256.7,261.9,266.9
XS GIS Cut Line= 3
     1810707.359      270277.423     1810839.657      270115.997
     1811691.611      269447.589
#Sta/Elev= 30
       0    1180     9.5 1176.94    28.5 1173.69    47.4 1169.95   104.4 1159.66
   113.8 1157.87  124.261155.528   132.8 1153.55   142.3 1151.94  150.491151.121
   170.8 1149.95   180.2 1149.11  205.591146.321     238 1142.96  250.63 1142.15
   257.5 1141.94     277 1141.89  1067.2 1141.93    1077 1142.04  1086.7 1142.36
  1106.2 1143.44  1125.7 1145.12    1155  1148.5  1164.8 1149.19    1194 1150.45
    1233 1153.06  1242.8 1153.59  1252.6 1153.86  1262.3 1153.62  1291.6    1152
#Mann= 7 ,-1 , 0
       0     .12       0  124.26    .016       0  150.49     .12       0
  205.59     .06       0  250.63     .04       0   257.5    .045       0
  1067.2     .06       0
Bank Sta=257.5,1067.2
XS Rating Curve= 0 ,0
Exp/Cntr=0.3,0.1

Type RM Length L Ch R = 1 ,15763.1 ,294.9,292.3,289.7
XS GIS Cut Line= 2
     1810809.233      270326.521     1811812.189      269845.218
#Sta/Elev= 30
       0 1177.99    19.5 1172.55      39 1167.48    48.8 1165.19    68.3 1161.18
    78.1 1159.62    87.8 1158.42  123.141154.869   126.9 1154.47   146.4 1150.59
   165.9 1148.36  186.561144.439  188.611144.103   195.2 1143.02   204.9  1142.2
   214.7 1141.93   234.2 1141.89   878.3 1141.89  936.251142.306   956.3 1142.67
   962.31143.025  970.431143.705   975.8 1144.27   985.6 1145.78  1014.9 1151.08
  1024.6 1152.53  1034.4 1153.41  1053.9 1154.76  1063.7  1155.7  1112.5 1162.01
#Mann= 9 ,-1 , 0
       0     .12       0  123.14    .016       0  186.56     .12       0
  188.61     .04       0   214.7    .045       0   878.3     .04       0
  936.25     .08       0   962.3     .04       0  970.43     .06       0
Bank Sta=214.7,878.3
XS Rating Curve= 0 ,0
Exp/Cntr=0.3,0.1

Type RM Length L Ch R = 1 ,15470.8 ,277.1,279.2,281.4
XS GIS Cut Line= 3
     1810905.122      270594.805     1811063.715      270572.256
     1812007.847      269979.499
#Sta/Elev= 30
       0    1196   21.051190.636   56.671178.727   75.661172.959   93.531168.353
   131.9 1159.95  148.291155.567   160.2  1152.4  184.691149.935   228.6 1143.75
  244.771142.244   248.2 1142.03   267.8 1141.89   805.6 1141.89  861.811143.034
   903.4 1144.48   955.71148.248   971.8 1148.92  1001.2 1149.02 1026.141150.788
  1079.4 1159.03 1130.95 1164.95 1172.481170.039  1196.7 1173.22    12071173.955
  1226.1 1174.06  1235.9 1177.14 1243.851180.656  1255.4 1184.97    1275 1189.85
#Mann= 17 ,-1 , 0
       0     .12       0   21.05     .06       0   56.67     .12       0
   75.66     .06       0   93.53     .12       0  148.29    .016       0
  184.69     .06       0  244.77     .04       0   248.2    .045       0
   805.6     .04       0  861.81     .08       0   955.7     .12       0
 1026.14     .06       0 1130.95     .12       0 1172.48     .08       0
    1207    .016       0 1243.85     .12       0
Bank Sta=248.2,805.6
XS Rating Curve= 0 ,0
Exp/Cntr=0.3,0.1

Type RM Length L Ch R = 1 ,15191.6 ,300,300,300
XS GIS Cut Line= 4
     1810978.278      270748.527     1811177.455       270780.61
     1811558.924      270589.876     1812169.371      270284.652
#Sta/Elev= 30
       0    1166    38.4 1161.15    86.5 1155.64   115.3 1151.82  129.511150.364
   144.1 1149.65  185.561148.546  269.221145.661  271.831145.588   366.5 1143.44
  451.741141.953   453.8 1141.93   473.2 1141.89   979.2 1141.96     989 1142.62
   998.7 1144.73 1010.221148.135  1018.2 1149.92 1072.761158.314  1102.61162.958
 1105.521163.363  1115.7 1164.17  1135.2 1164.28  1143.61166.251    1145 1166.58
  1164.5 1175.04  1174.2 1177.47  1242.5 1189.67  1291.2 1197.86  1310.7 1201.99
#Mann= 13 ,-1 , 0
       0     .12       0  129.51    .016       0  185.56     .06       0
  269.22     .08       0  271.83     .06       0  451.74     .04       0
   453.8    .045       0   979.2     .04       0 1010.22     .06       0
 1072.76     .12       0  1102.6     .08       0 1105.52    .016       0
  1143.6     .12       0
Bank Sta=453.8,979.2
XS Rating Curve= 0 ,0
Exp/Cntr=0.3,0.1

Type RM Length L Ch R = 1 ,14891.6 ,147.4,142.9,138.4
XS GIS Cut Line= 2
     1811395.389      271007.053     1812138.308      270635.594
#Sta/Elev= 30
       0    1154     9.8 1152.87    19.5 1152.07    39.1 1151.34   43.961150.953
    48.9 1150.56   66.51 1148.63    78.2 1147.18   107.5 1143.28  109.471143.097
   117.3 1142.37     127 1141.93   136.8 1141.89   644.9  1141.9   654.7 1142.03
   664.5 1142.48  667.891142.795   674.3 1143.39     684 1144.61  731.811151.213
   742.7 1152.34   752.4 1152.67   762.2 1152.22     772 1152.13  775.881153.496
   781.8 1155.58   791.5 1159.97   801.3  1162.5   811.1 1163.87   830.6    1166
#Mann= 9 ,-1 , 0
       0    .016       0   43.96     .12       0   66.51     .06       0
  109.47     .04       0     127    .045       0   644.9     .04       0
  667.89     .06       0  731.81    .016       0  775.88     .12       0
Bank Sta=127,644.9
XS Rating Curve= 0 ,0
Exp/Cntr=0.3,0.1

Type RM Length L Ch R = 1 ,14748.7 ,124.7,124,123.9
XS GIS Cut Line= 2
     1811606.511      271102.919     1812163.001       270670.51
#Sta/Elev= 30
       0 1152.41     9.8 1149.42    19.6 1146.74    29.4 1145.38    39.2 1144.82
   61.731143.958   107.7 1142.82   127.2 1142.14     137 1141.95     186 1141.87
     509 1141.95  515.291142.053   518.8 1142.11   528.6 1142.78   538.3 1143.79
  563.191146.997   577.5 1148.89   587.3 1150.03   597.1  1150.8  600.121150.865
   606.9 1151.01   616.6 1150.04   626.4 1150.49  628.261150.925   636.2 1152.78
     646 1155.69   655.8 1157.32   665.6 1158.58   675.4 1160.08   704.7 1164.88
#Mann= 8 ,-1 , 0
       0     .06       0   61.73     .04       0     137    .045       0
     509     .04       0  515.29     .06       0  563.19     .08       0
  600.12    .016       0  628.26     .12       0
Bank Sta=137,509
XS Rating Curve= 0 ,0
Exp/Cntr=0.3,0.1

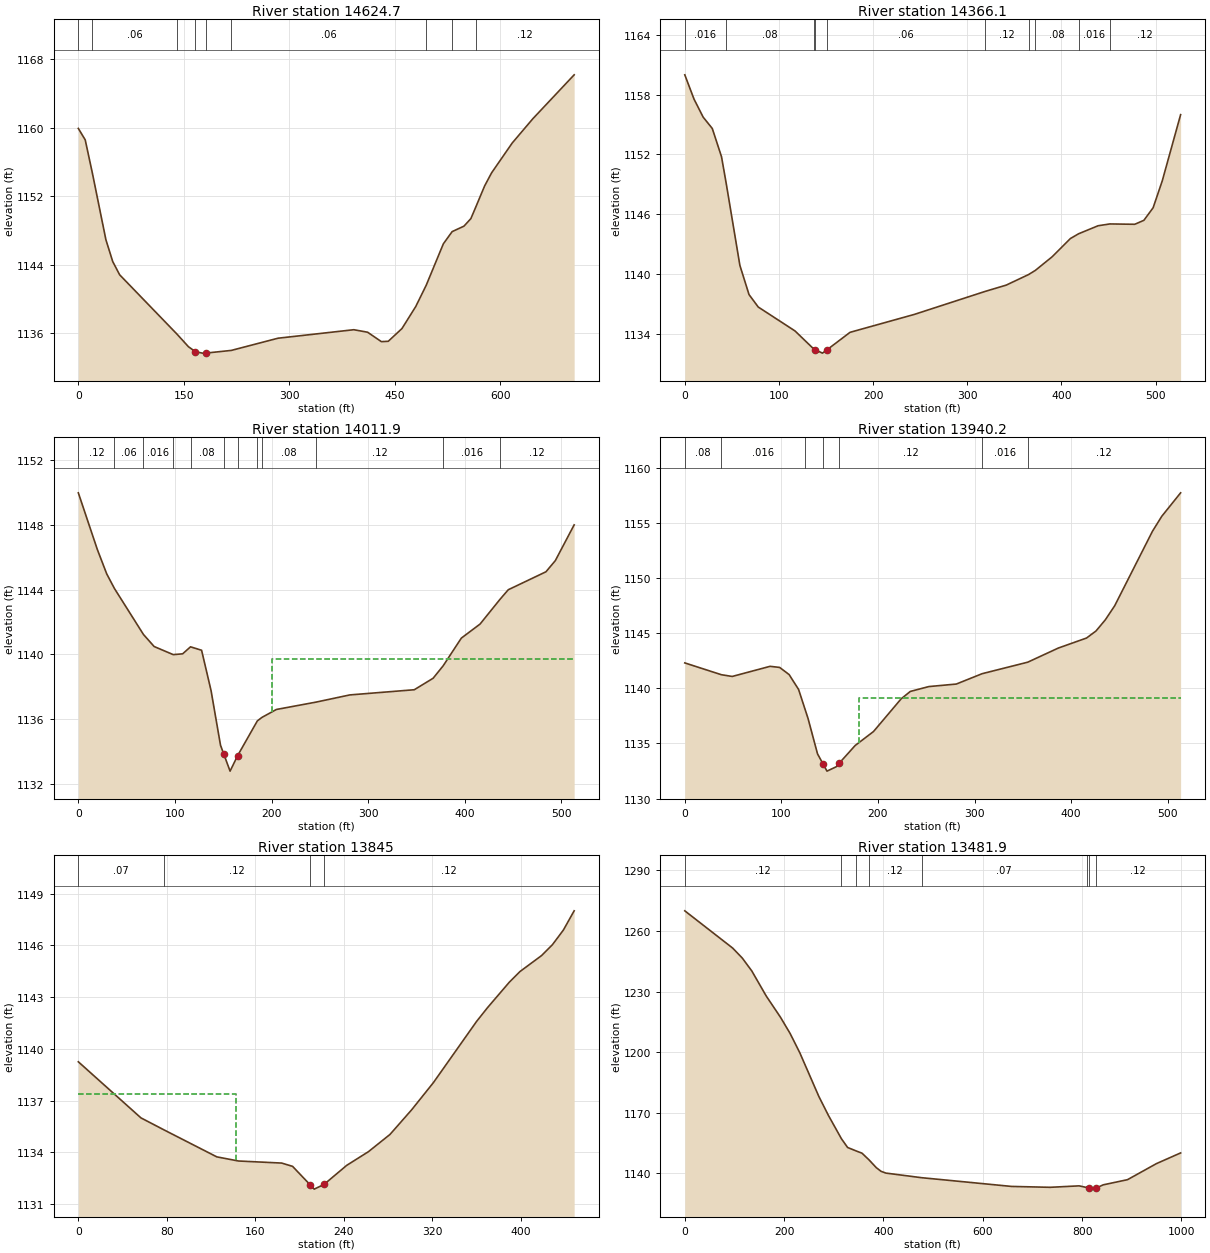
Type RM Length L Ch R = 1 ,14624.7 ,262.8,258.6,253.1
XS GIS Cut Line= 2
     1811692.598      271192.139     1812249.088       270759.73
#Sta/Elev= 30
       0 1159.91     9.8 1158.57   19.981154.691    39.2 1146.92    48.9 1144.38
    58.7 1142.84  139.861135.947   156.6 1134.44   166.4 1133.87   176.2  1133.7
  181.87 1133.71  217.461134.017   283.8 1135.44   391.5 1136.43   411.1 1136.14
   430.7 1135.04   440.5 1135.08     460 1136.57   479.6 1139.14  494.341141.598
   518.8 1146.45  531.271147.872   548.1 1148.51   557.9 1149.39  564.611150.684
   577.5 1153.21   587.3 1154.72   616.6  1158.2     646 1161.04   704.7 1166.16
#Mann= 9 ,-1 , 0
       0    .016       0   19.98     .06       0  139.86     .12       0
   166.4    .045       0  181.87     .12       0  217.46     .06       0
  494.34     .08       0  531.27    .016       0  564.61     .12       0
Bank Sta=166.4,181.87
XS Rating Curve= 0 ,0
Exp/Cntr=0.3,0.1

Type RM Length L Ch R = 1 ,14366.1 ,365.6,354.2,331.7
XS GIS Cut Line= 2
     1811911.051      271370.372     1812242.346      270961.156
#Sta/Elev= 30
       0    1160     9.8 1157.56    19.5 1155.75    29.2 1154.61      39 1151.77
   43.841149.167    58.5 1140.86    68.2 1137.93      78 1136.68     117 1134.28
  137.251132.437   138.3 1132.39   146.2 1132.05  150.671132.359   175.5 1134.14
   243.8 1135.94  319.261138.258   341.3 1138.88  364.981139.938  372.161140.354
     390 1141.72   409.5 1143.56  418.161144.037   438.8 1144.84  451.351145.024
   477.8 1144.99   487.5 1145.39   497.3 1146.65     507 1149.35   526.5    1156
#Mann= 10 ,-1 , 0
       0    .016       0   43.84     .08       0  137.25     .12       0
   138.3    .045       0  150.67     .06       0  319.26     .12       0
  364.98     .06       0  372.16     .08       0  418.16    .016       0
  451.35     .12       0
Bank Sta=138.3,150.67
XS Rating Curve= 0 ,0
Exp/Cntr=0.3,0.1

Type RM Length L Ch R = 1 ,14011.9 ,71.8,71.7,78.6
XS GIS Cut Line= 4
     1812250.751      271562.168     1812277.645      271397.479
     1812186.708      271241.067     1812296.607      271117.372
#Sta/Elev= 30
       0 1149.98    19.6 1146.49    29.4 1144.97   37.411144.064   67.431141.225
    78.5 1140.48   98.27 1139.98     108 1140.03  116.151140.463   127.6 1140.25
   137.4 1137.76   147.2 1134.38   150.61133.829   157.1 1132.78  164.961133.743
  185.321135.884  190.111136.101     205 1136.59  245.821137.042   281.1 1137.49
   347.8 1137.81   367.3 1138.52  377.731139.292   396.5    1141   415.9 1141.87
  436.451143.392   445.1 1143.99   484.1  1145.1   493.8 1145.79   513.3    1148
#Mann= 12 ,-1 , 0
       0     .12       0   37.41     .06       0   67.43    .016       0
   98.27     .12       0  116.15     .08       0   150.6    .045       0
  164.96     .08       0  185.32     .12       0  190.11     .08       0
  245.82     .12       0  377.73    .016       0  436.45     .12       0
#XS Ineff= 2 , 0
                          200.82         1139.69
Permanent Ineff=
       F       F
Bank Sta=150.6,164.96
XS Rating Curve= 0 ,0
Exp/Cntr=0.3,0.1

Type RM Length L Ch R = 1 ,13940.2 ,103.6,95.2,88.3
XS GIS Cut Line= 4
     1812323.668      271559.043     1812350.561      271394.354
     1812259.625      271237.942     1812369.524      271114.247
#Sta/Elev= 30
       0 1142.32   37.931141.246    49.1 1141.09    88.3 1142.01    98.2 1141.91
     108 1141.26   117.8 1139.91  124.621138.073   127.6 1137.27   137.4 1134.06
  143.38  1133.1   147.2 1132.49   157.1  1132.9  159.851133.206   176.4 1134.82
   195.4 1136.09     224 1139.06   233.5 1139.73   252.6 1140.17   281.1  1140.4
  307.821141.341  354.991142.385   386.7 1143.67   415.9 1144.58   425.7 1145.22
   435.4 1146.24   445.1 1147.52   484.1 1154.27   493.8 1155.64   513.3 1157.77
#Mann= 7 ,-1 , 0
       0     .08       0   37.93    .016       0  124.62     .12       0
  143.38    .045       0  159.85     .12       0  307.82    .016       0
  354.99     .12       0
#XS Ineff= 2 , 0
                          179.88         1139.13
Permanent Ineff=
       F       F
Bank Sta=143.38,159.85
XS Rating Curve= 0 ,0
Exp/Cntr=0.3,0.1

Type RM Length L Ch R = 1 ,13845   ,352.9,363.1,372.9
XS GIS Cut Line= 3
     1812426.632      271616.638     1812473.366      271584.617
      1812390.43      271201.872
#Sta/Elev= 23
       0 1139.25    56.6    1136   77.661135.297   125.2 1133.74   144.8  1133.5
   183.9 1133.38   193.7 1133.19  209.371132.136   213.3 1131.87   222.1 1132.14
   242.7 1133.25   262.3 1134.04   281.8 1135.04   301.4 1136.47     321 1138.04
   360.2  1141.6     370 1142.39   389.5 1143.85   399.3 1144.48   418.9 1145.41
   428.7 1146.04   438.5 1146.88   448.3    1148
#Mann= 4 ,-1 , 0
       0     .07       0   77.66     .12       0  209.37    .045       0
   222.1     .12       0
#XS Ineff= 2 , 0
          142.71 1137.41
Permanent Ineff=
       F       F
Bank Sta=209.37,222.1
XS Rating Curve= 0 ,0
Exp/Cntr=0.3,0.1

Type RM Length L Ch R = 1 ,13481.9 ,215.3,216.8,218
XS GIS Cut Line= 3
     1812144.956      272091.781     1812545.103       272029.92
      1812666.02      271448.981
#Sta/Elev= 30
       0    1270    96.4 1251.53   115.7  1246.6     135 1240.16   163.9  1227.8
   192.8 1217.19   212.1 1209.18   231.4 1199.73   269.9 1177.99   289.2 1168.58
  315.361157.027   327.8  1152.7  345.171150.962   356.7 1149.88  370.741146.601
   385.6 1142.68   395.3 1140.86   404.9    1140  476.581137.722   657.8 1133.39
   735.6 1132.95     794 1133.67  808.951132.872   813.5 1132.45   823.2 1132.05
  827.871132.554   842.6 1134.18   891.3 1136.73   949.6 1144.69   998.3    1150
#Mann= 8 ,-1 , 0
       0     .12       0  315.36     .08       0  345.17    .016       0
  370.74     .12       0  476.58     .07       0  808.95     .12       0
   813.5    .045       0  827.87     .12       0
Bank Sta=813.5,827.87
XS Rating Curve= 0 ,0
Exp/Cntr=0.3,0.1