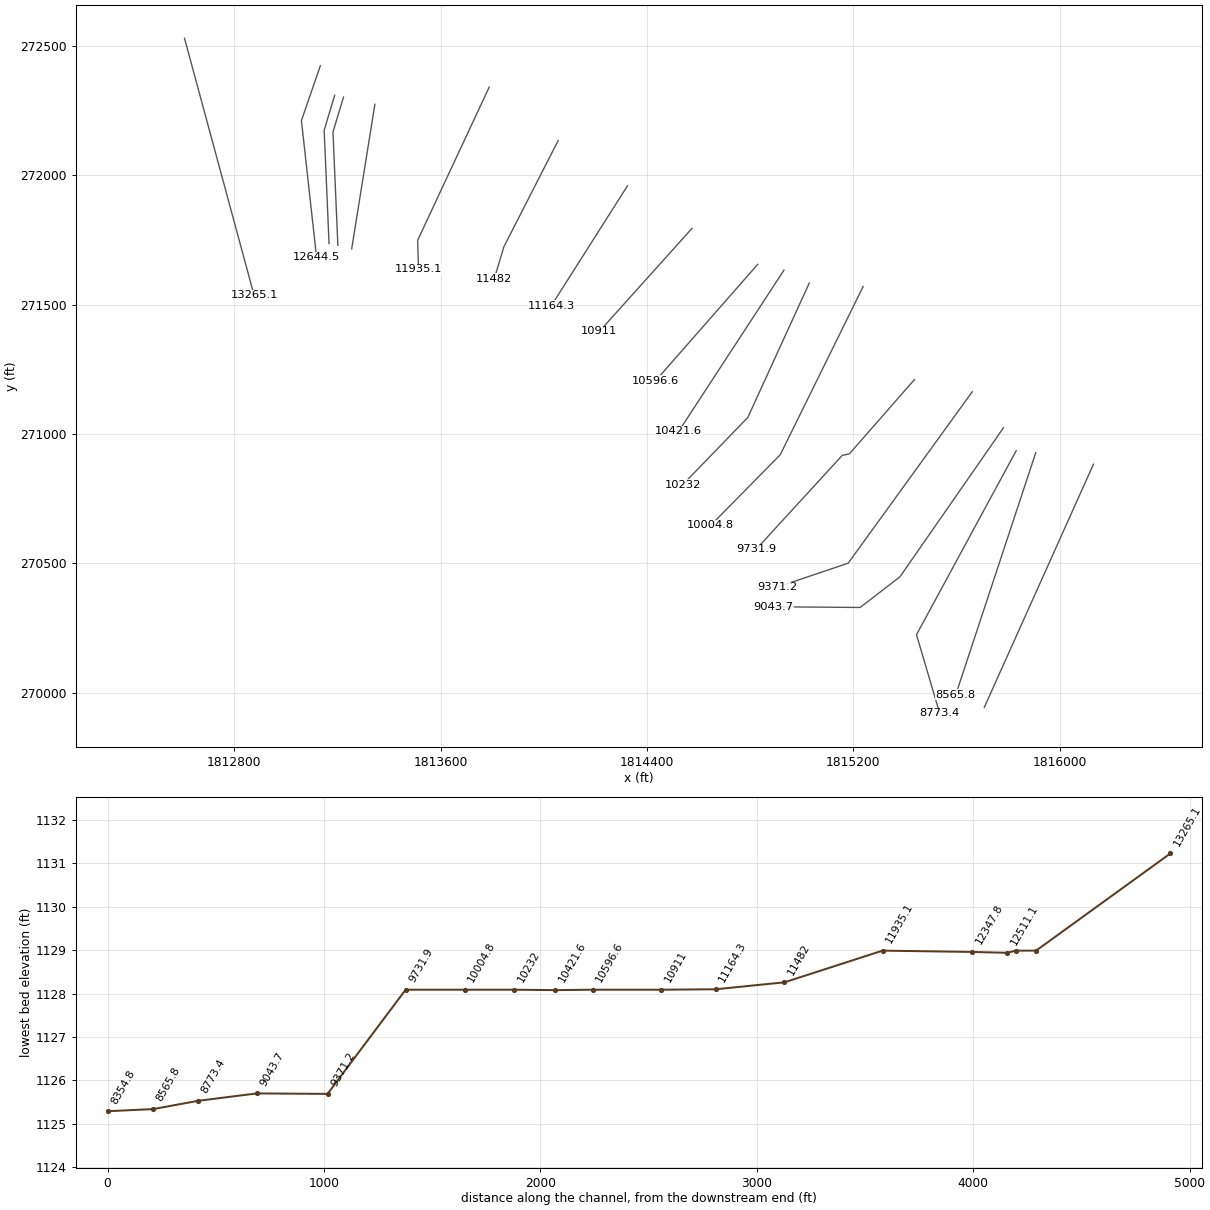
HEC-RAS study PLEASNTCK.prj: PLEASNTCK

--- PLEASNTCK.g01 (geometry) --- (continued)

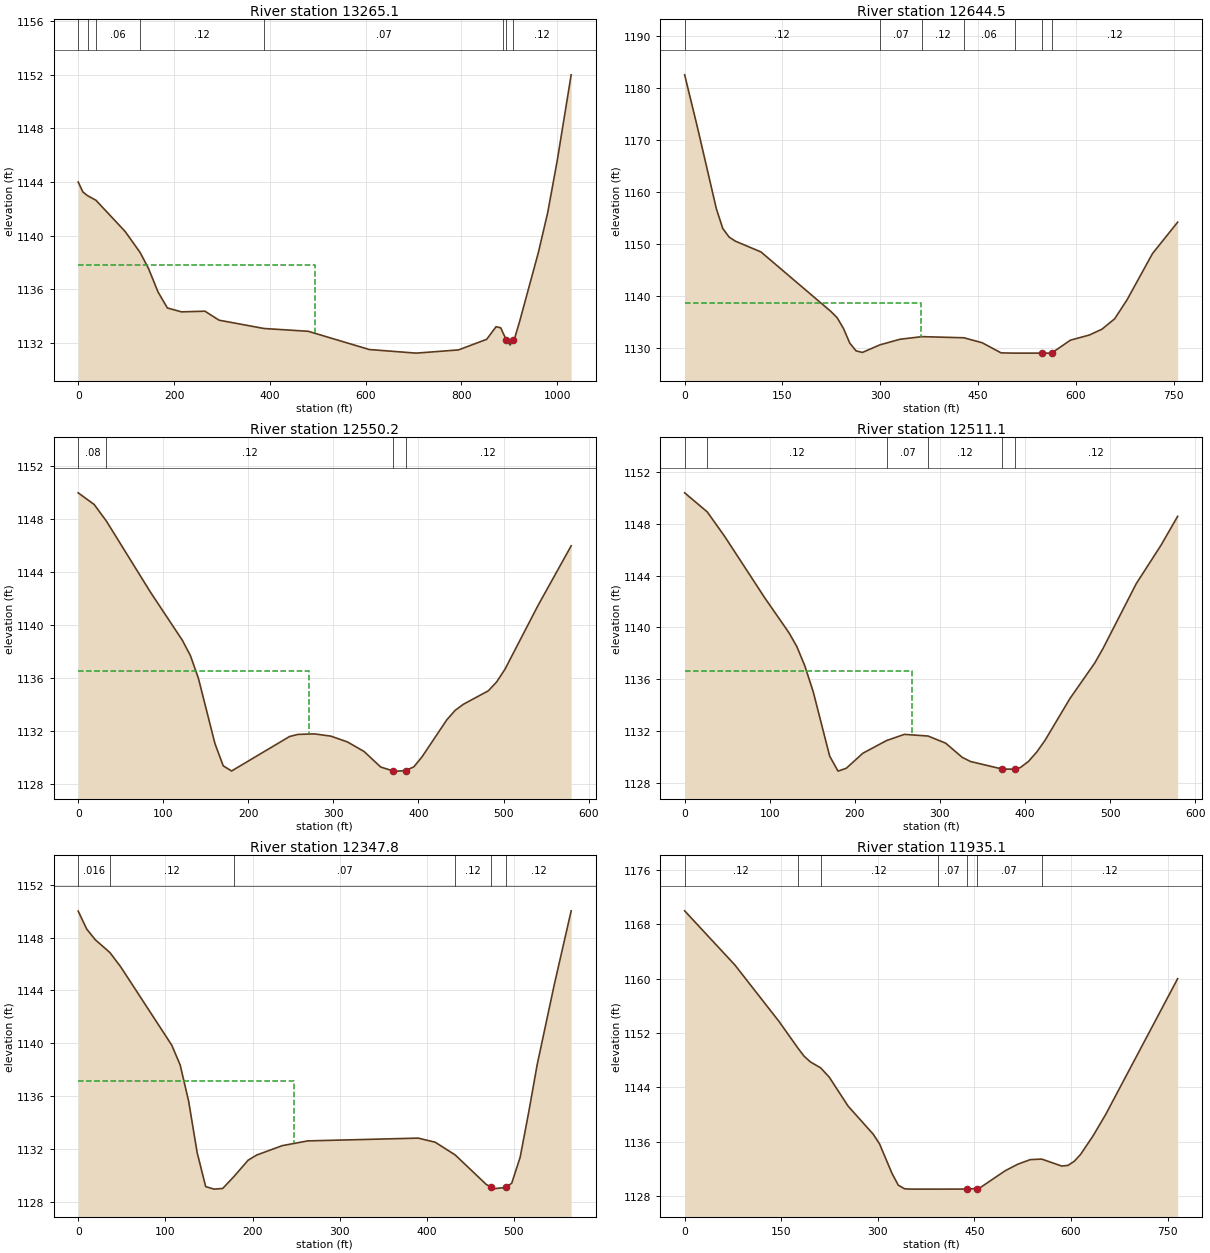
Type RM Length L Ch R = 1 ,13265.1 ,626.9,620.6,615.3
XS GIS Cut Line= 2
     1812606.965      272529.788     1812876.638      271536.675
#Sta/Elev= 30
       0    1144     9.8 1143.26    19.51142.983      371142.641      98 1140.31
  129.411138.735     147 1137.53   166.6  1135.8   186.2  1134.6   215.6 1134.31
   264.6 1134.36     294 1133.69  387.981133.068   480.2 1132.86   607.6  1131.5
   705.6 1131.23   793.9 1131.47   852.7 1132.26   872.3  1133.2   882.1 1133.12
  887.641132.673   893.81132.238   901.7 1131.84  908.671132.233   911.5 1132.39
   921.3 1133.57   960.5 1138.72   980.1 1141.72   999.7 1145.54  1029.1    1152
#Mann= 8 ,-1 , 0
       0     .06       0    19.5    .016       0      37     .06       0
  129.41     .12       0  387.98     .07       0  887.64     .12       0
   893.8    .045       0  908.67     .12       0
#XS Ineff= 2 , 0
          493.84 1137.81
Permanent Ineff=
       F       F
Bank Sta=893.8,908.67
XS Rating Curve= 0 ,0
Exp/Cntr=0.3,0.1

Type RM Length L Ch R = 1 ,12644.5 ,88,94.4,93.2
XS GIS Cut Line= 3
     1813133.575      272423.845     1813060.159      272211.987
     1813118.892      271683.391
#Sta/Elev= 30
       0 1182.61    19.5 1172.56    48.7 1156.77    58.5    1153    68.2 1151.35
      78 1150.55     117 1148.49   224.2 1137.03   233.9 1135.81   243.6 1133.74
   253.2 1130.93   262.9 1129.43   272.6 1129.12  299.57 1130.59   330.6 1131.67
  364.161132.167  428.271131.947   456.3 1130.99   485.3 1129.04   504.6 1128.99
  506.19 1128.99  547.48 1128.99   562.7 1128.99   591.7 1131.49   620.7 1132.48
     640  1133.6   659.4 1135.59   678.7  1139.3   717.4 1148.15   756.1 1154.22
#Mann= 7 ,-1 , 0
       0     .12       0  299.57     .07       0  364.16     .12       0
  428.27     .06       0  506.19     .12       0  547.48    .045       0
   562.7     .12       0
#XS Ineff= 2 , 0
          363.04 1138.62
Permanent Ineff=
       F       F
Bank Sta=547.48,562.7
XS Rating Curve= 0 ,0
Exp/Cntr=0.3,0.1

Type RM Length L Ch R = 1 ,12550.2 ,37.3,39.1,61.4
XS GIS Cut Line= 3
     1813189.126      272309.769     1813148.304      272174.469
     1813167.234      271736.696
#Sta/Elev= 30
       0 1149.99    18.8 1149.11   33.241147.851    84.8 1142.51   122.5 1138.86
   131.9 1137.71   141.3    1136   160.8 1131.06   170.5 1129.39   180.3    1129
   248.4  1131.6   258.2 1131.76   277.6  1131.8   297.1 1131.63   316.6 1131.19
   336.1 1130.47   355.6  1129.3  370.011129.006     375 1128.99   384.8 1129.03
   394.5 1129.31   404.2 1130.07   433.4 1132.87   443.2 1133.58   452.9 1134.04
   482.1 1135.05   491.9 1135.72   501.6 1136.67   540.6  1141.5   579.5 1145.99
#Mann= 4 ,-1 , 0
       0     .08       0   33.24     .12       0  370.01    .045       0
   384.8     .12       0
#XS Ineff= 2 , 0
          271.05 1136.57
Permanent Ineff=
       F       F
Bank Sta=370.01,384.8
XS Rating Curve= 0 ,0
Exp/Cntr=0.3,0.1

Type RM Length L Ch R = 1 ,12511.1 ,168.3,163.3,136.1
XS GIS Cut Line= 3
     1813223.283      272302.781     1813182.461      272167.482
     1813201.392      271729.708
#Sta/Elev= 30
       0 1150.37   26.561148.904    47.1 1147.01    94.2 1142.28   122.5 1139.61
   131.9 1138.53   141.3 1137.04   151.1 1135.06   170.5 1130.09   180.3 1128.94
     190 1129.16   209.5 1130.32  237.381131.296   258.2 1131.77  286.141131.643
   306.9 1131.09   326.3    1130   336.1 1129.68   373.11129.103  388.151129.088
   394.5 1129.21   404.2 1129.69     414 1130.42   423.7 1131.32   452.9 1134.53
   482.1 1137.27   491.9  1138.4   530.8 1143.37     560 1146.34   579.5 1148.56
#Mann= 6 ,-1 , 0
       0    .016       0   26.56     .12       0  237.38     .07       0
  286.14     .12       0   373.1    .045       0  388.15     .12       0
#XS Ineff= 2 , 0
          266.74 1136.66
Permanent Ineff=
       F       F
Bank Sta=373.1,388.15
XS Rating Curve= 0 ,0
Exp/Cntr=0.3,0.1

Type RM Length L Ch R = 1 ,12347.8 ,418.9,412.7,405
XS GIS Cut Line= 2
     1813344.878      272274.738     1813255.072      271716.267
#Sta/Elev= 30
       0    1150     9.8 1148.64    19.5 1147.84   36.411146.861    48.8 1145.78
   107.3 1139.86     117 1138.36   126.8 1135.59   136.5 1131.72   146.3 1129.15
     156 1128.96   165.8 1129.01  178.571129.903     195 1131.15   204.8 1131.54
   234.1 1132.25   263.3 1132.61   390.1 1132.82   409.6 1132.51  432.551131.547
   468.1 1129.32  473.61 1129.12   477.9    1129  490.79 1129.09   497.4 1129.41
   507.1 1131.38   516.9 1134.79   526.6 1138.38   546.1  1144.4   565.6 1150.02
#Mann= 6 ,-1 , 0
       0    .016       0   36.41     .12       0  178.57     .07       0
  432.55     .12       0  473.61    .045       0  490.79     .12       0
#XS Ineff= 2 , 0
          247.64 1137.12
Permanent Ineff=
       F       F
Bank Sta=473.61,490.79
XS Rating Curve= 0 ,0
Exp/Cntr=0.3,0.1

Type RM Length L Ch R = 1 ,11935.1 ,460.2,453.1,451.8
XS GIS Cut Line= 3
     1813788.067      272341.229     1813510.717      271749.053
     1813514.075      271637.427
#Sta/Elev= 30
       0    1170    78.1 1162.01   146.4 1153.72  175.561149.819   185.4 1148.59
   195.2 1147.74  211.341146.851   224.5  1145.5   253.8 1141.23   292.8 1137.09
   302.6 1135.67   322.1 1131.29   331.8 1129.57   341.6 1129.04   351.4 1128.99
  392.67 1128.99   438.6    1129   453.6 1129.08   458.7 1129.19   497.8  1131.7
   517.3 1132.66   536.8 1133.34  554.631133.414   585.6 1132.39   595.4 1132.49
   605.1  1133.1   614.9 1134.11   634.4 1136.86   653.9    1140   765.6    1160
#Mann= 7 ,-1 , 0
       0     .12       0  175.56    .016       0  211.34     .12       0
  392.67     .07       0   438.6    .045       0   453.6     .07       0
  554.63     .12       0
Bank Sta=438.6,453.6
XS Rating Curve= 0 ,0
Exp/Cntr=0.3,0.1

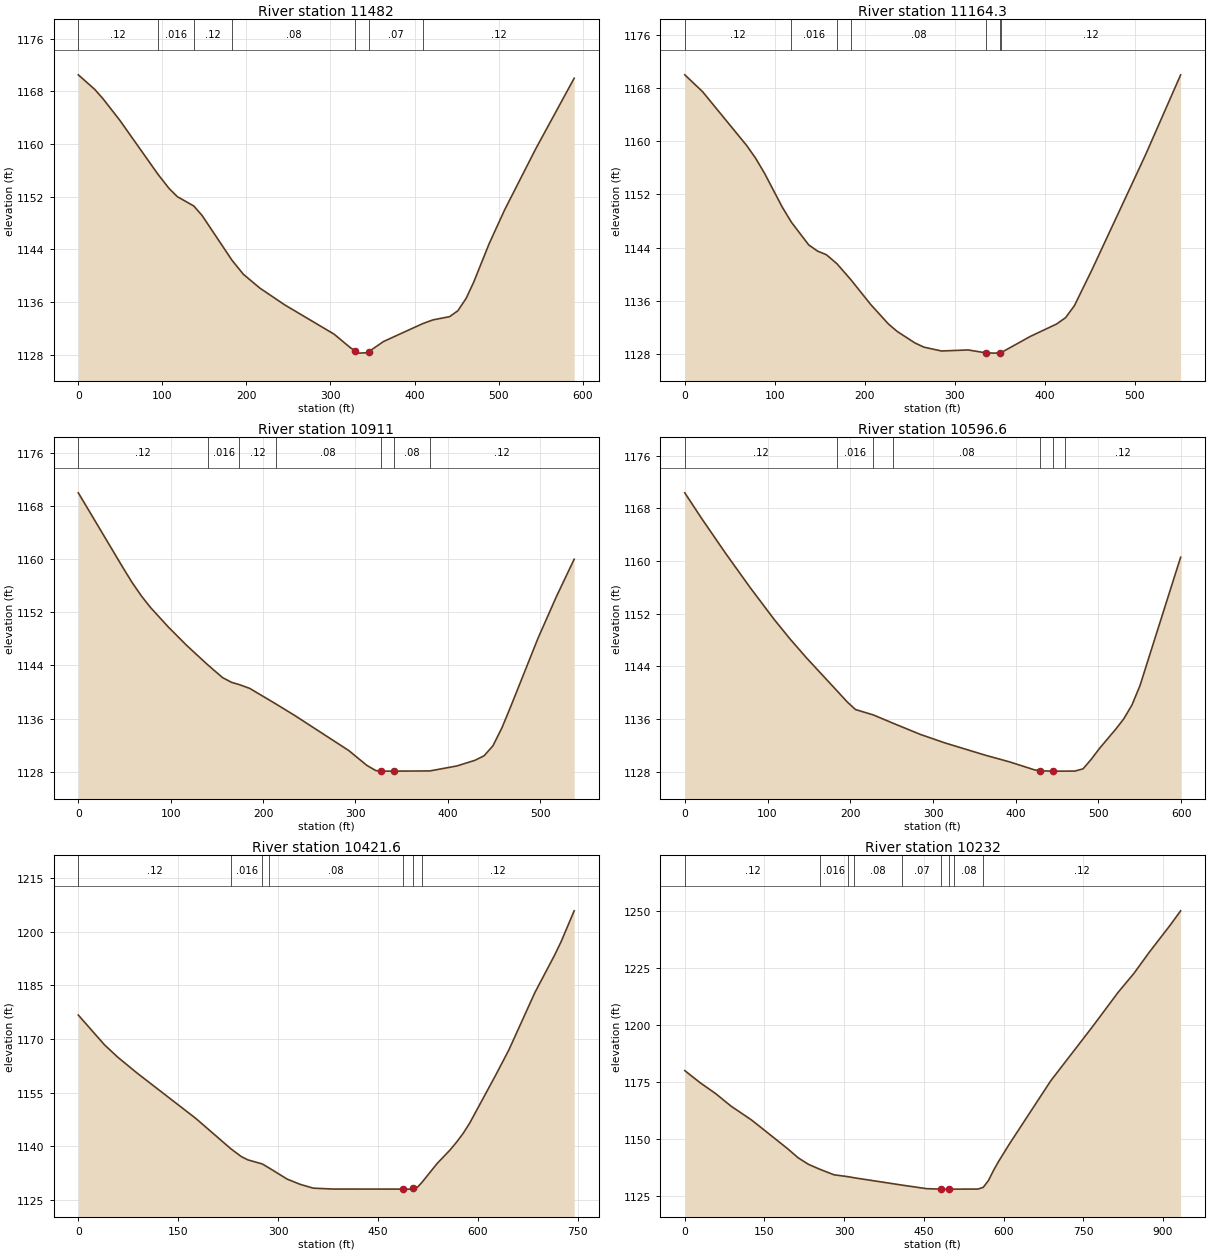
Type RM Length L Ch R = 1 ,11482   ,317.2,317.6,316.6
XS GIS Cut Line= 3
     1814055.549      272135.013     1813845.244      271724.447
     1813807.869      271601.423
#Sta/Elev= 30
       0 1170.52    19.6  1168.3    29.4 1166.88    49.1 1163.66   94.951155.385
     108 1153.26   117.8 1152.02  137.361150.603   147.2 1149.17  182.791142.372
   196.3 1140.24   215.9 1138.14   245.4  1135.6   304.3 1131.14   323.9 1129.06
  329.641128.591   333.7 1128.26   343.5 1128.32  345.761128.503   363.2 1130.03
  409.591132.733     422 1133.31   441.7  1133.8   451.5 1134.69   461.3 1136.56
   470.5 1139.07   488.8 1144.89   507.2 1150.02     544 1159.24   589.9    1170
#Mann= 7 ,-1 , 0
       0     .12       0   94.95    .016       0  137.36     .12       0
  182.79     .08       0  329.64    .045       0  345.76     .07       0
  409.59     .12       0
Bank Sta=329.64,345.76
XS Rating Curve= 0 ,0
Exp/Cntr=0.3,0.1

Type RM Length L Ch R = 1 ,11164.3 ,257.1,253.4,249.2
XS GIS Cut Line= 2
     1814324.271      271959.934     1814028.295      271495.394
#Sta/Elev= 30
       0    1170    19.7 1167.47    68.8 1159.35    78.7 1157.44    88.5  1155.2
   108.2  1150.1  118.411147.815   137.7 1144.39   147.5 1143.46   157.4 1142.91
  169.071141.553   184.7 1139.12   206.6 1135.41   226.2 1132.49   236.1 1131.35
   255.7 1129.63   265.6    1129   285.2 1128.42   314.8 1128.58   334.4 1128.14
   344.3  1128.1  350.441128.188   351.81128.207   383.6  1130.6   413.1 1132.49
     423 1133.44   432.8 1135.24   452.5  1140.7   511.5 1157.86   550.8 1169.99
#Mann= 7 ,-1 , 0
       0     .12       0  118.41    .016       0  169.07     .12       0
   184.7     .08       0   334.4    .045       0  350.44     .08       0
   351.8     .12       0
Bank Sta=334.4,350.44
XS Rating Curve= 0 ,0
Exp/Cntr=0.3,0.1

Type RM Length L Ch R = 1 ,10911   ,314.3,314.4,311.6
XS GIS Cut Line= 2
     1814574.421      271795.458     1814215.065      271396.732
#Sta/Elev= 30
       0    1170    48.8 1158.62    58.6 1156.42    68.3 1154.47    78.1 1152.74
    97.6 1149.77   117.1 1147.05  140.081144.101   156.2 1142.17   165.9 1141.46
  174.391141.114   185.4 1140.56  213.571138.235   234.2 1136.48   292.8 1131.19
   312.3 1128.96   322.1 1128.17  327.471128.125   331.8 1128.09   341.6 1128.09
  380.62 1128.12   409.9 1128.87   429.4 1129.72   439.2 1130.39   448.9 1131.91
   458.7 1134.64   468.4 1137.91   497.7 1148.11   517.2 1154.26   536.8    1160
#Mann= 7 ,-1 , 0
       0     .12       0  140.08    .016       0  174.39     .12       0
  213.57     .08       0  327.47    .045       0   341.6     .08       0
  380.62     .12       0
Bank Sta=327.47,341.6
XS Rating Curve= 0 ,0
Exp/Cntr=0.3,0.1

Type RM Length L Ch R = 1 ,10596.6 ,172.5,175,178.3
XS GIS Cut Line= 2
     1814828.916      271656.087     1814433.017      271206.165
#Sta/Elev= 30
       0 1170.38    19.6 1166.63    49.1 1161.23    78.6 1156.05   108.1 1151.13
   127.7  1148.1   147.4 1145.26   184.31140.252   196.5 1138.58   206.3 1137.45
  227.87 1136.63  251.89 1135.36   284.9 1133.66   314.4 1132.38   363.5  1130.5
     393 1129.48   422.5 1128.29   429.9 1128.15   442.1 1128.09   444.9 1128.09
  459.02 1128.09   471.6  1128.1   481.4 1128.44   491.2 1129.88   501.1 1131.52
   520.7 1134.44   530.5 1136.02   540.4 1138.12   550.2 1141.09   599.3 1160.59
#Mann= 7 ,-1 , 0
       0     .12       0   184.3    .016       0  227.87     .06       0
  251.89     .08       0   429.9    .045       0   444.9     .08       0
  459.02     .12       0
Bank Sta=429.9,444.9
XS Rating Curve= 0 ,0
Exp/Cntr=0.3,0.1

Type RM Length L Ch R = 1 ,10421.6 ,185.8,189.6,199.9
XS GIS Cut Line= 2
     1814930.899      271633.997     1814522.912      271011.167
#Sta/Elev= 30
       0 1176.67    39.2 1168.39    58.8 1164.98    88.2 1160.49   176.3 1147.84
  229.031139.349   244.9 1137.15   254.7 1136.24  276.081135.123  285.941134.049
   313.5 1130.89   333.1 1129.42   352.7 1128.36   382.1  1128.1   486.9 1128.09
   499.6 1128.08  503.071128.277   509.4 1128.63  515.581129.866   538.8 1135.23
   558.4 1139.05   568.2 1141.24     578 1143.67   587.8 1146.54     627 1159.99
   646.6 1166.96   685.8 1183.03   715.2 1193.39     725 1197.16   744.6 1205.78
#Mann= 7 ,-1 , 0
       0     .12       0  229.03    .016       0  276.08     .12       0
  285.94     .08       0   486.9    .045       0  503.07     .08       0
  515.58     .12       0
Bank Sta=486.9,503.07
XS Rating Curve= 0 ,0
Exp/Cntr=0.3,0.1

Type RM Length L Ch R = 1 ,10232   ,228.6,227.3,219.3
XS GIS Cut Line= 3
     1815028.829       271583.73     1814790.623      271064.317
     1814538.473      270804.785
#Sta/Elev= 30
       0    1180    29.1 1174.66    58.1 1169.93    87.2 1164.42   125.9 1158.33
   193.7 1145.78   213.1 1141.86   232.4    1139  254.461136.756   280.9 1134.37
  307.651133.526  318.731133.068  409.15 1129.84   455.2 1128.29   481.9 1128.09
   496.9 1128.09   507.1 1128.09   552.1 1128.12  561.831128.889   571.4 1131.79
   581.2 1136.33     591 1140.35   610.6 1147.72   688.8 1175.53     767 1199.12
   815.9 1214.37   845.3 1222.57   874.6 1231.95   913.7 1243.73   933.3    1250
#Mann= 9 ,-1 , 0
       0     .12       0  254.46    .016       0  307.65     .12       0
  318.73     .08       0  409.15     .07       0   481.9    .045       0
   496.9     .07       0   507.1     .08       0  561.83     .12       0
Bank Sta=481.9,496.9
XS Rating Curve= 0 ,0
Exp/Cntr=0.3,0.1

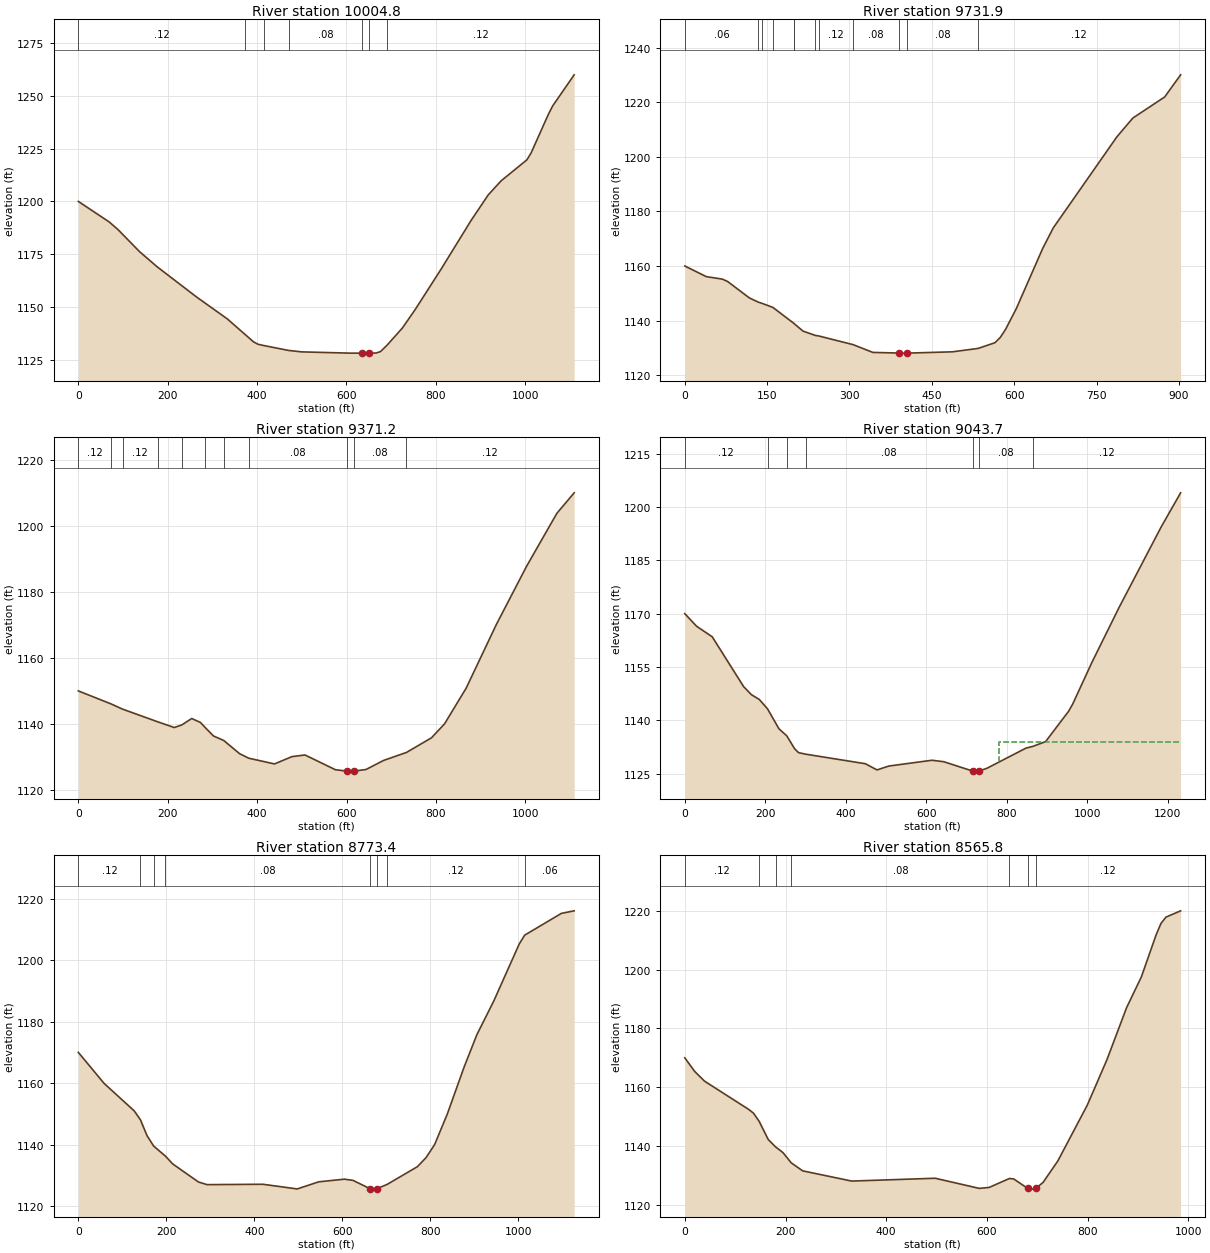
Type RM Length L Ch R = 1 ,10004.8 ,287.5,272.8,258.9
XS GIS Cut Line= 3
     1815237.768       271570.59     1814916.583      270920.521
      1814646.55      270647.114
#Sta/Elev= 30
       0    1200    68.6 1190.34    88.2 1186.76   137.2 1176.15   176.4    1169
   264.6 1154.69   333.2 1144.34  371.851137.179   391.9 1133.46   401.7 1132.31
  415.151131.681  470.29 1129.37   499.7 1128.68   607.5 1128.09   635.5 1128.09
   650.5 1128.09   666.3 1128.14   676.1 1128.82  690.65 1131.83   725.1    1140
   753.9  1148.8   811.6 1167.87   878.8 1190.99   917.2  1203.1     946 1209.76
  1003.7 1219.71  1013.3 1223.07  1051.7 1241.27  1061.3 1245.24  1109.4    1260
#Mann= 7 ,-1 , 0
       0     .12       0  371.85    .016       0  415.15     .12       0
  470.29     .08       0   635.5    .045       0   650.5     .08       0
  690.65     .12       0
Bank Sta=635.5,650.5
XS Rating Curve= 0 ,0
Exp/Cntr=0.3,0.1

Type RM Length L Ch R = 1 ,9731.9  ,347.1,360.7,368.7
XS GIS Cut Line= 4
     1815436.497      271210.684     1815184.524      270923.861
     1815156.747      270917.785     1814822.999      270554.881
#Sta/Elev= 30
       0    1160    39.2  1156.1    68.5 1155.19    78.3 1154.28   117.5 1148.32
  133.85 1146.77  141.121146.282  160.431144.841  198.241139.057   198.91138.942
   215.4 1136.15  237.931134.567  243.861134.386  306.451131.204   342.6 1128.35
   390.6 1128.12   400.7 1128.09   405.6 1128.09   487.6 1128.57  534.291129.809
   564.9 1131.89   574.6 1133.81   584.2 1136.75   603.6 1144.27   651.9  1166.4
   671.2 1173.95   787.2 1207.32   816.2 1214.18   874.2  1221.9   903.2    1230
#Mann= 12 ,-1 , 0
       0     .06       0  133.85     .12       0  141.12     .06       0
  160.43     .08       0  198.24     .06       0   198.9    .016       0
  237.93     .06       0  243.86     .12       0  306.45     .08       0
   390.6    .045       0   405.6     .08       0  534.29     .12       0
Bank Sta=390.6,405.6
XS Rating Curve= 0 ,0
Exp/Cntr=0.3,0.1

Type RM Length L Ch R = 1 ,9371.2  ,332.2,327.5,320.7
XS GIS Cut Line= 3
      1815660.88      271163.851     1815179.709      270501.139
      1814904.94       270408.71
#Sta/Elev= 30
       0 1149.99   73.011146.065   98.911144.471  178.071140.607   214.5  1138.9
  231.321139.677   253.5 1141.63     273 1140.45  284.111138.848   302.2 1136.34
  325.111134.986   360.7 1130.97  381.131129.605   438.7 1127.87   477.7 1130.08
     507 1130.58   575.2  1126.1   601.2  1125.7   604.5 1125.69   616.2 1125.69
   643.5 1126.19   682.5 1128.92  733.731131.342   789.7 1135.77     819    1140
   867.3 1150.81   934.9 1170.11  1002.6 1187.78  1070.2 1203.78  1108.9    1210
#Mann= 11 ,-1 , 0
       0     .12       0   73.01     .06       0   98.91     .12       0
  178.07     .06       0  231.32     .12       0  284.11    .016       0
  325.11     .12       0  381.13     .08       0   601.2    .045       0
   616.2     .08       0  733.73     .12       0
Bank Sta=601.2,616.2
XS Rating Curve= 0 ,0
Exp/Cntr=0.3,0.1

Type RM Length L Ch R = 1 ,9043.7  ,260.2,270.3,273.3
XS GIS Cut Line= 4
     1815781.735      271024.425     1815380.432      270448.505
     1815226.167       270329.97     1814890.638      270332.674
#Sta/Elev= 30
       0    1170    29.2 1166.47    68.2 1163.49   146.2 1149.47   165.7  1147.2
   185.2 1145.86  205.711143.205     234  1137.6  253.361135.636     273 1131.98
   282.7  1130.9  300.151130.474   448.5 1127.79   477.7 1126.04     507 1127.13
   614.2 1128.76   643.4 1128.35   715.4 1125.72   721.4  1125.7   730.4 1125.73
   750.6 1126.49   847.8 1132.18   864.4 1132.65   896.5    1134     954 1142.59
   963.6 1144.51  1011.5 1156.27  1078.6 1171.64  1184.1 1194.49    1232    1204
#Mann= 7 ,-1 , 0
       0     .12       0  205.71    .016       0  253.36     .12       0
  300.15     .08       0   715.4    .045       0   730.4     .08       0
   864.4     .12       0
#XS Ineff= 2 , 0
                          780.19         1134.02
Permanent Ineff=
       F       F
Bank Sta=715.4,730.4
XS Rating Curve= 0 ,0
Exp/Cntr=0.3,0.1

Type RM Length L Ch R = 1 ,8773.4  ,203.4,207.6,211.5
XS GIS Cut Line= 3
     1815831.127      270936.022      1815444.59      270224.682
     1815534.545      269920.618
#Sta/Elev= 30
       0 1169.99    58.5 1159.91   126.8    1151  141.151148.067   156.1 1142.92
  171.11 1139.54   197.91136.264   214.6 1133.71   273.1 1127.84   292.6 1126.99
   419.4 1127.11   497.4 1125.59   546.2  1127.9   604.7 1128.77   624.2 1128.37
   663.3 1125.64     673 1125.53  678.021125.642   701.81127.068   770.6 1132.84
   790.1 1135.76   809.6    1140   838.4 1149.92   876.8 1165.28   905.7 1175.75
   944.1  1186.7  1001.8 1205.19 1014.211208.087  1097.8 1215.18  1126.7    1216
#Mann= 8 ,-1 , 0
       0     .12       0  141.15    .016       0  171.11     .12       0
   197.9     .08       0   663.3    .045       0  678.02     .08       0
   701.8     .12       0 1014.21     .06       0
Bank Sta=663.3,678.02
XS Rating Curve= 0 ,0
Exp/Cntr=0.3,0.1

Type RM Length L Ch R = 1 ,8565.8  ,465.7,211,206.3
XS GIS Cut Line= 2
     1815906.755      270927.823     1815596.975      269993.208
#Sta/Elev= 30
       0    1170    19.5 1165.41      39 1162.09   126.7 1152.48   136.5 1151.16
  147.491148.455   165.7 1142.22  180.391139.681     195 1137.76  211.341134.284
     234 1131.56   331.4 1128.08   497.2 1129.04   584.9 1125.59   604.4 1125.92
  644.641128.957   653.2  1128.8  681.081125.571   692.2 1125.34     6971125.554
   711.6 1127.66   740.9 1134.96   799.4 1153.96   838.4 1169.41   877.4  1187.1
   906.6  1197.5   935.9  1211.8   945.6 1215.72   955.4 1217.85   984.6    1220
#Mann= 7 ,-1 , 0
       0     .12       0  147.49    .016       0  180.39     .12       0
  211.34     .08       0  644.64     .12       0  681.08    .045       0
     697     .12       0
Bank Sta=681.08,697
XS Rating Curve= 0 ,0
Exp/Cntr=0.3,0.1

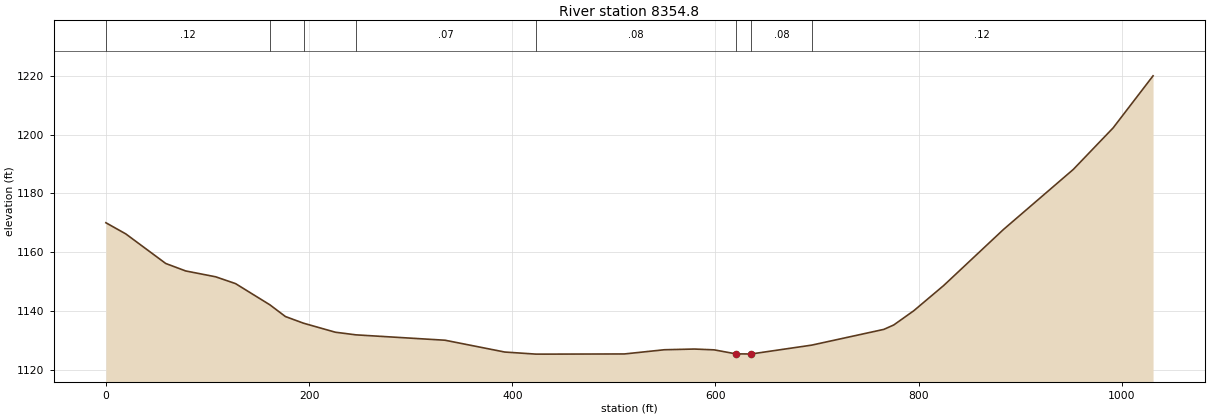
Type RM Length L Ch R = 1 ,8354.8  ,143.7,398.7,399.3
XS GIS Cut Line= 2
     1816130.587      270883.591     1815707.359      269943.803
#Sta/Elev= 30
       0    1170    19.6  1166.2    58.9 1156.14    78.5  1153.6     108 1151.61
   127.6 1149.29   161.41142.073   176.7 1138.08  194.55 1135.81   225.8 1132.75
  246.12 1131.85   333.8 1130.02   392.6    1126  422.951125.299   431.9 1125.29
   510.4 1125.35   549.7 1126.78   579.2 1127.02   598.8 1126.74   620.1 1125.38
   635.1 1125.34  694.69 1128.35   765.7 1133.71   775.5 1135.22   795.1 1140.03
   824.6 1148.63   883.4 1167.69   952.2 1188.15   991.4 1202.28  1030.7    1220
#Mann= 8 ,-1 , 0
       0     .12       0   161.4    .016       0  194.55     .12       0
  246.12     .07       0  422.95     .08       0   620.1    .045       0
   635.1     .08       0  694.69     .12       0
Bank Sta=620.1,635.1
XS Rating Curve= 0 ,0
Exp/Cntr=0.3,0.1