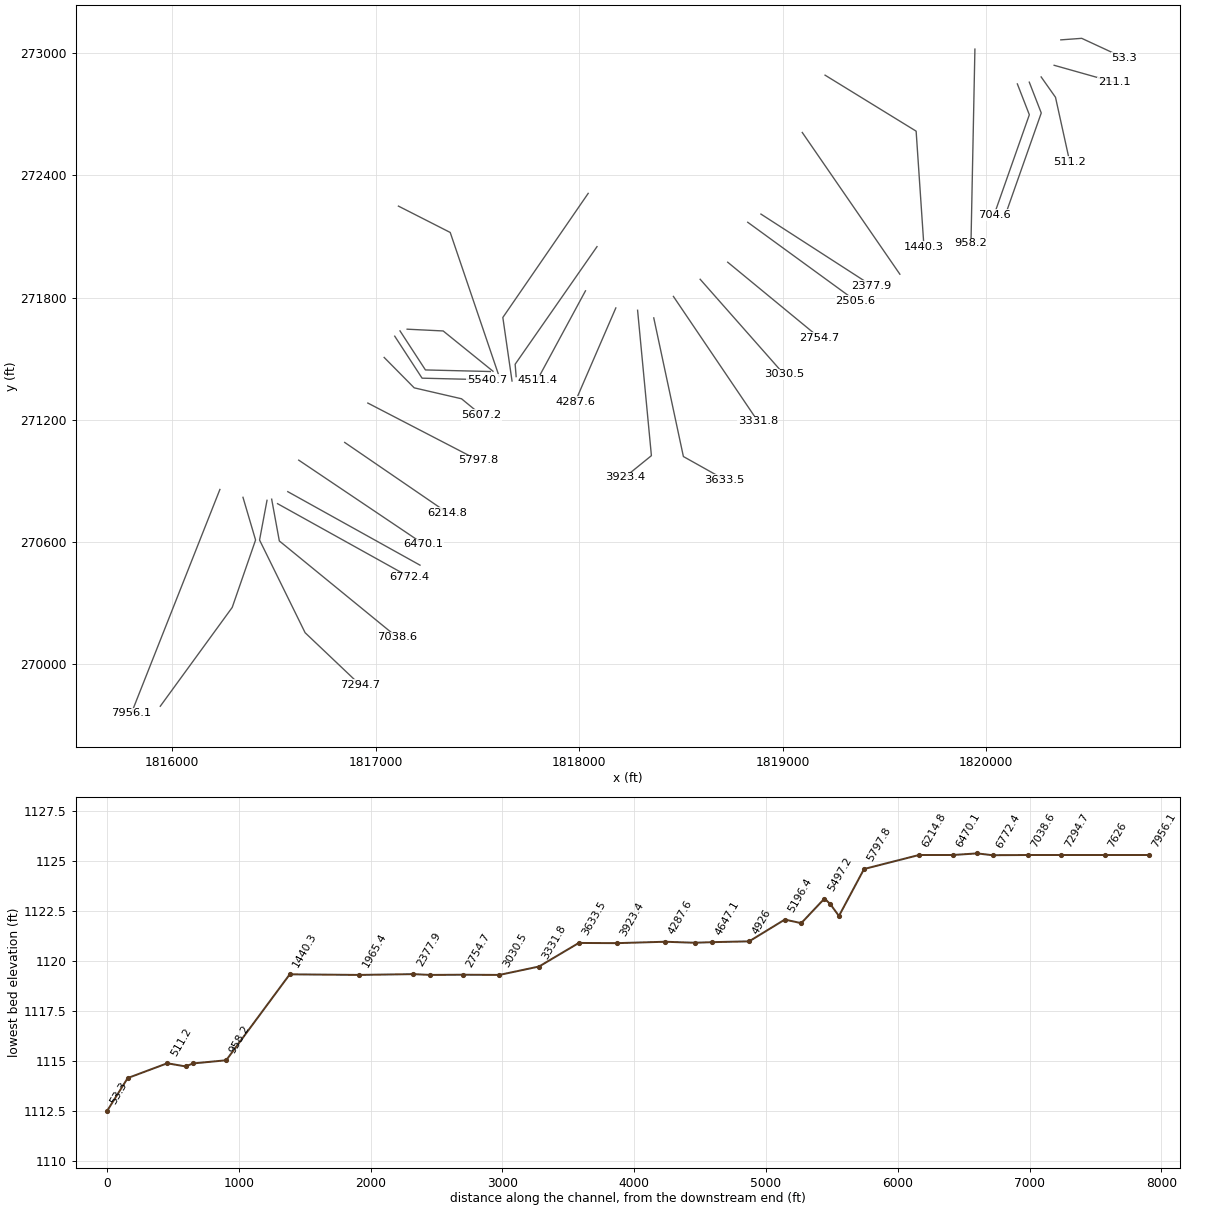
HEC-RAS study PLEASNTCK.prj: PLEASNTCK

--- PLEASNTCK.g01 (geometry) --- (continued)

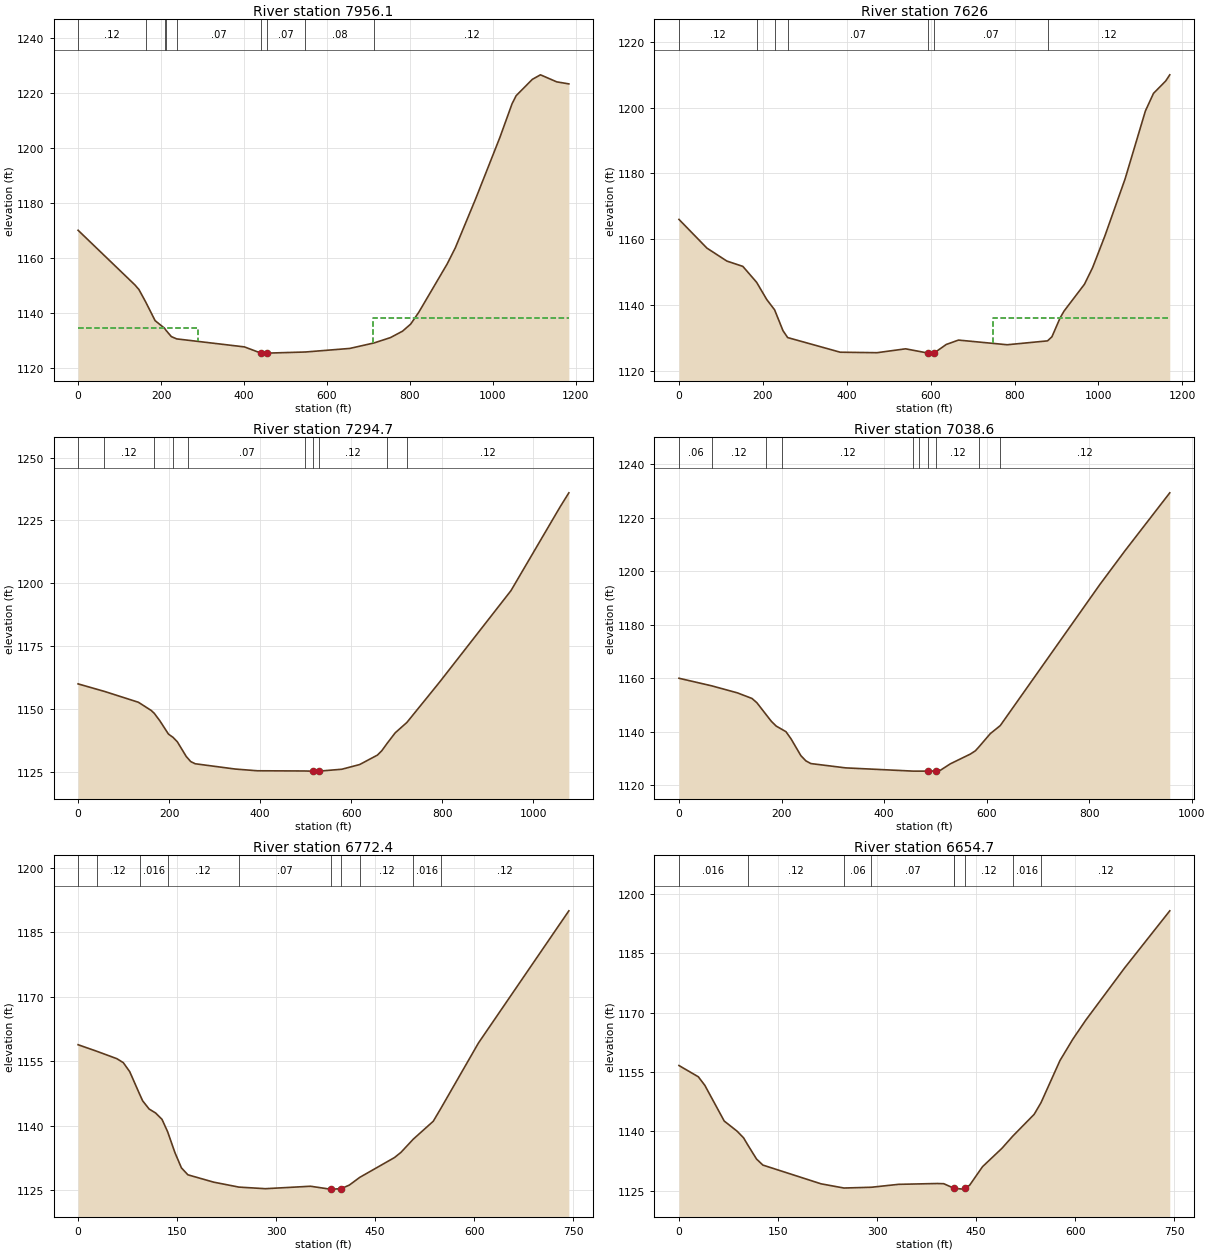
Type RM Length L Ch R = 1 ,7956.1  ,335.5,330.1,324.2
XS GIS Cut Line= 2
     1816233.691      270856.787     1815798.461      269756.454
#Sta/Elev= 30
       0    1170   136.9 1150.13   146.7 1148.44  163.051143.896   185.8  1137.1
  208.531134.339  212.221133.548   224.9  1131.3  237.73 1130.47     401 1127.56
   440.7 1125.31   449.8 1125.29   455.7 1125.29  548.23  1125.7   655.2    1127
  713.481128.991     753 1130.93   782.3 1133.28   801.9 1135.85   821.4 1140.15
   889.9 1157.74   909.5 1163.59   958.4 1181.38    1017 1203.78  1046.4 1216.05
  1056.2 1218.97  1095.3 1224.92  1114.8 1226.56  1153.9 1224.01  1183.3 1223.26
#Mann= 9 ,-1 , 0
       0     .12       0  163.05    .016       0  208.53     .06       0
  212.22     .12       0  237.73     .07       0   440.7    .045       0
   455.7     .07       0  548.23     .08       0  713.48     .12       0
#XS Ineff= 2 , 0
          288.54 1134.59  712.27            1138
Permanent Ineff=
       F       F
Bank Sta=440.7,455.7
XS Rating Curve= 0 ,0
Exp/Cntr=0.3,0.1

Type RM Length L Ch R = 1 ,7626    ,306.2,331.3,355.7
XS GIS Cut Line= 4
     1816347.123      270818.182     1816409.029      270608.411
     1816294.194      270277.041     1815940.698      269791.513
#Sta/Elev= 30
       0    1166    66.6 1157.26   114.1 1153.32   152.2  1151.7  185.09 1146.85
   209.2 1141.61  227.981138.465   247.9 1132.13  259.061130.028   384.3 1125.57
     472 1125.42   540.2  1126.6   593.5 1125.31   598.5 1125.29   608.5 1125.35
   637.2 1127.93   666.3 1129.26   782.5 1127.84  878.561129.022   889.1 1130.27
   908.5    1136   918.1 1138.12   966.6 1146.26     986 1151.31    1015 1160.86
  1063.4  1178.3  1111.9 1199.02  1131.2 1204.38  1160.3 1208.14    1170 1210.02
#Mann= 7 ,-1 , 0
       0     .12       0  185.09    .016       0  227.98     .12       0
  259.06     .07       0   593.5    .045       0   608.5     .07       0
  878.56     .12       0
#XS Ineff= 2 , 0
                           748.9            1136
Permanent Ineff=
       F       F
Bank Sta=593.5,608.5
XS Rating Curve= 0 ,0
Exp/Cntr=0.3,0.1

Type RM Length L Ch R = 1 ,7294.7  ,246.9,256.1,263.3
XS GIS Cut Line= 4
     1816465.233      270803.461     1816428.589      270608.287
      1816652.48      270152.805     1816922.055      269896.899
#Sta/Elev= 30
       0    1160    57.91157.004   132.4 1152.69   160.8  1149.4  167.331148.282
   179.7 1145.28   198.6    1140   208.71138.704   218.1 1136.93   237.6  1131.1
  241.881130.222   247.4 1129.09   257.2 1128.22     345 1126.12   393.8 1125.43
   497.61125.349   510.9 1125.29   514.9 1125.29   529.9 1125.29   579.2 1126.04
   618.3  1127.9   657.3 1131.66   667.1 1133.43  678.611136.307   696.4 1140.52
   722.11144.653   794.2 1160.77   950.7  1197.1  1058.2 1230.29  1077.8    1236
#Mann= 10 ,-1 , 0
       0     .06       0    57.9     .12       0  167.33    .016       0
   208.7     .06       0  241.88     .07       0   497.6     .12       0
   514.9    .045       0   529.9     .12       0  678.61    .016       0
   722.1     .12       0
Bank Sta=514.9,529.9
XS Rating Curve= 0 ,0
Exp/Cntr=0.3,0.1

Type RM Length L Ch R = 1 ,7038.6  ,261.4,266.3,270.5
XS GIS Cut Line= 3
     1816488.116      270809.055     1816525.736      270603.796
     1817105.378       270130.09
#Sta/Elev= 30
       0 1159.99   64.311157.137   113.8 1154.54   142.3 1152.45   151.8 1150.88
  169.211146.584   180.2 1143.89   189.7 1142.11  201.751140.788   208.7 1140.02
   218.4  1137.4   237.8 1131.06   247.6 1129.11   257.3 1128.11   325.3  1126.5
   456.51125.295   461.4 1125.29  468.97 1125.29   486.6 1125.29   501.6 1125.35
   510.1 1125.64   529.5 1128.04   568.4 1131.67   578.1 1132.88  584.791134.287
   607.3 1139.31  626.611142.296   821.2 1195.09   869.8  1207.6   957.3 1229.28
#Mann= 10 ,-1 , 0
       0     .06       0   64.31     .12       0  169.21    .016       0
  201.75     .12       0   456.5     .07       0  468.97     .12       0
   486.6    .045       0   501.6     .12       0  584.79    .016       0
  626.61     .12       0
Bank Sta=486.6,501.6
XS Rating Curve= 0 ,0
Exp/Cntr=0.3,0.1

Type RM Length L Ch R = 1 ,6772.4  ,117.2,117.7,115.8
XS GIS Cut Line= 2
        1816517.      270786.959     1817166.642      270425.805
#Sta/Elev= 30
       0 1158.86   28.081157.355    58.7 1155.62    68.5 1154.69    78.2  1152.6
   93.42 1147.29    97.8 1145.82   107.6 1143.91   117.4 1142.99   127.1 1141.51
   135.61138.639   146.7 1133.77   156.5 1130.23   166.3 1128.61   205.4  1126.9
  243.561125.752   283.6 1125.38   352.1 1125.95   381.4 1125.28   383.1 1125.28
   398.1 1125.37   410.8 1126.22   426.71128.024   479.2 1132.62     489 1133.83
  507.691136.904   537.9 1141.06  549.391144.039   606.4 1159.27   743.3    1190
#Mann= 10 ,-1 , 0
       0     .06       0   28.08     .12       0   93.42    .016       0
   135.6     .12       0  243.56     .07       0   383.1    .045       0
   398.1     .07       0   426.7     .12       0  507.69    .016       0
  549.39     .12       0
Bank Sta=383.1,398.1
XS Rating Curve= 0 ,0
Exp/Cntr=0.3,0.1

Type RM Length L Ch R = 1 ,6654.7  ,185.6,184.6,184
XS GIS Cut Line= 2
     1816567.347      270845.987     1817216.989      270484.833
#Sta/Elev= 30
       0 1156.64    29.3 1153.79    39.1 1151.64    68.5  1142.6      88 1140.03
    97.8 1138.35  103.881136.638   117.4 1132.99   127.1 1131.45   215.2 1126.71
  249.781125.649  291.511125.845   332.5 1126.58   391.2 1126.79     401 1126.74
  416.281125.602  416.831125.573   430.3 1125.37  433.911125.725   440.1 1126.34
   459.7 1131.05     489 1135.68   505.41138.756   537.9 1144.29  548.251147.235
     577  1157.9   596.6 1163.34   616.1 1168.13   674.8 1181.31   743.3 1195.78
#Mann= 9 ,-1 , 0
       0    .016       0  103.88     .12       0  249.78     .06       0
  291.51     .07       0  416.28     .12       0  416.83    .045       0
  433.91     .12       0   505.4    .016       0  548.25     .12       0
Bank Sta=416.83,433.91
XS Rating Curve= 0 ,0
Exp/Cntr=0.3,0.1

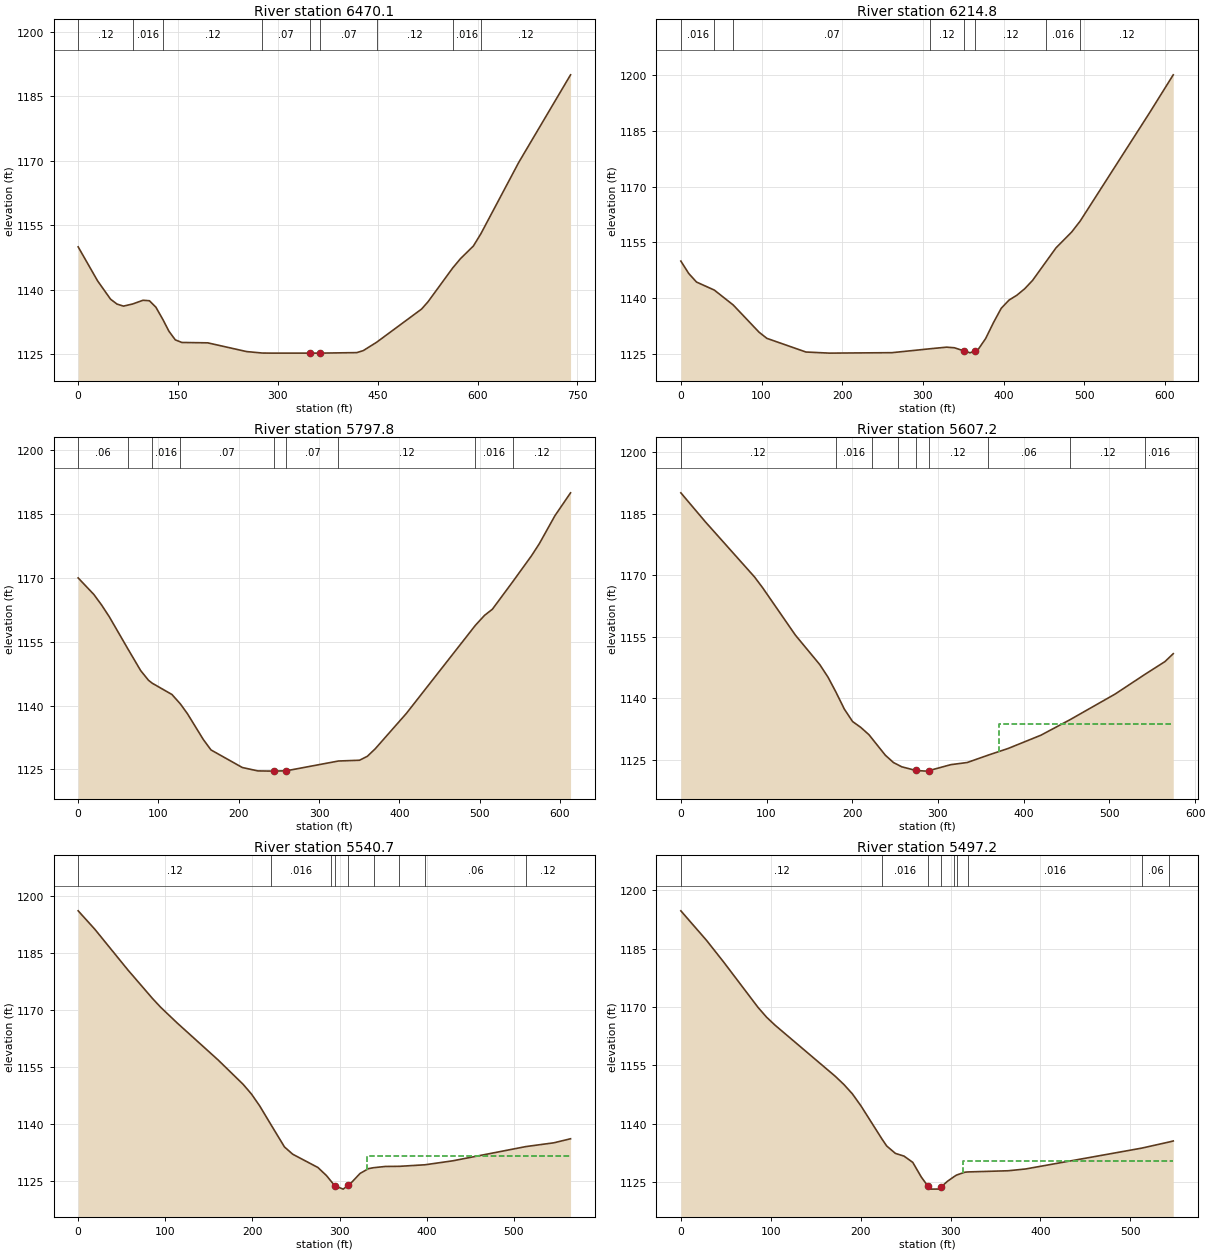
Type RM Length L Ch R = 1 ,6470.1  ,255.8,255.3,253.8
XS GIS Cut Line= 2
     1816621.121      271000.854     1817235.047      270587.974
#Sta/Elev= 30
       0    1150    29.2 1142.09    48.7 1137.83    58.4 1136.69    68.1 1136.22
   81.97 1136.72    97.4 1137.58   107.1 1137.47   116.8 1135.97  127.591133.022
   136.3  1130.4     146 1128.37   155.8 1127.77   194.7 1127.68   253.1 1125.65
  276.771125.311     292 1125.29   348.7 1125.29   363.7 1125.29   418.6 1125.41
   428.3 1125.87  448.461127.821     516 1135.54   525.7 1137.24  562.711145.086
   574.4 1147.25   593.8  1150.2  604.871152.994     662 1169.65   739.8    1190
#Mann= 9 ,-1 , 0
       0     .12       0   81.97    .016       0  127.59     .12       0
  276.77     .07       0   348.7    .045       0   363.7     .07       0
  448.46     .12       0  562.71    .016       0  604.87     .12       0
Bank Sta=348.7,363.7
XS Rating Curve= 0 ,0
Exp/Cntr=0.3,0.1

Type RM Length L Ch R = 1 ,6214.8  ,413.9,417,416.7
XS GIS Cut Line= 2
     1816847.039      271087.844     1817350.694      270742.991
#Sta/Elev= 30
       0    1150     9.7 1146.69    19.4 1144.37    41.51142.216   64.961138.206
    96.9 1130.92   106.6 1129.26     155 1125.59   184.1 1125.29   261.6 1125.41
  308.911126.459   329.4 1126.89   339.1 1126.73  351.16 1125.87   358.5 1125.38
  365.181125.917   368.2 1126.16   377.9 1129.23   387.6 1133.51   397.2 1137.34
   406.9 1139.54   416.6 1140.84   426.3 1142.58     436 1144.81  452.891149.886
   465.1 1153.56   484.4 1157.78     4951160.731   581.3  1189.9   610.4    1200
#Mann= 8 ,-1 , 0
       0    .016       0    41.5     .12       0   64.96     .07       0
  308.91     .12       0  351.16    .045       0  365.18     .12       0
  452.89    .016       0     495     .12       0
Bank Sta=351.16,365.18
XS Rating Curve= 0 ,0
Exp/Cntr=0.3,0.1

Type RM Length L Ch R = 1 ,5797.8  ,184.8,190.6,196.2
XS GIS Cut Line= 2
     1816960.675      271281.378     1817505.016      270999.261
#Sta/Elev= 30
       0    1170    19.5 1166.12    29.2 1163.63    38.9 1160.83   61.441153.475
    77.8 1148.23    87.6 1145.94   92.18 1145.26   116.8  1142.6  127.351140.367
   136.2 1138.05   155.7 1132.06   165.4 1129.57   204.4 1125.44   223.8 1124.64
   243.3 1124.59  259.321124.675  324.041126.966   350.4 1127.15   360.1 1128.08
   369.8 1129.82   408.7 1138.16   494.71158.882     506  1161.2   515.8 1162.65
  540.821169.032   564.4 1175.19   574.2 1178.04   593.6 1184.61   613.1    1190
#Mann= 9 ,-1 , 0
       0     .06       0   61.44     .12       0   92.18    .016       0
  127.35     .07       0   243.3    .045       0  259.32     .07       0
  324.04     .12       0   494.7    .016       0  540.82     .12       0
Bank Sta=243.3,259.32
XS Rating Curve= 0 ,0
Exp/Cntr=0.3,0.1

Type RM Length L Ch R = 1 ,5607.2  ,61.4,66.4,71.1
XS GIS Cut Line= 4
     1817040.948      271505.514     1817188.517      271356.209
     1817421.156      271302.389     1817518.378      271222.528
#Sta/Elev= 30
       0 1190.11    28.6 1183.04    85.9 1169.61    95.4 1166.97   133.6 1155.42
   162.2 1148.19   171.8 1145.12  180.791141.581   190.8 1137.35   200.4 1134.33
   209.9 1132.91   219.5 1131.12  222.791130.251   238.6 1126.12   248.1 1124.33
     2531123.804   257.7  1123.3   274.2  1122.4   286.3 1122.24   289.2 1122.35
     315 1123.82   334.1 1124.34  358.311126.119   381.8 1127.76   420.1    1131
     4541134.774   506.8 1141.05  541.93  1145.9   564.8 1148.95   574.5 1150.88
#Mann= 9 ,-1 , 0
       0     .12       0  180.79    .016       0  222.79     .06       0
     253     .12       0   274.2    .045       0   289.2     .12       0
  358.31     .06       0     454     .12       0  541.93    .016       0
#XS Ineff= 2 , 0
                           370.9         1133.78
Permanent Ineff=
       F       F
Bank Sta=274.2,289.2
XS Rating Curve= 0 ,0
Exp/Cntr=0.3,0.1

Type RM Length L Ch R = 1 ,5540.7  ,43.1,43.5,45.8
XS GIS Cut Line= 3
     1817092.906      271609.977     1817227.241      271403.697
     1817545.905      271395.955
#Sta/Elev= 30
       0    1196    18.9 1191.22    56.8 1180.53    85.2 1172.98    94.7 1170.64
   113.6 1166.52     161  1156.7   189.4 1150.36   198.8 1147.84   208.3 1144.71
  221.731139.586   236.7 1133.93   246.2 1132.01   275.1 1128.52   284.8 1126.42
  290.551124.811   294.5 1123.71   304.1 1122.84  309.851123.898   313.8 1124.63
   323.4 1126.96   333.1 1128.23  338.961128.472   352.4  1128.8   368.51128.833
  398.041129.242   429.7 1130.28  513.861134.034   545.6 1135.01   564.9 1136.08
#Mann= 9 ,-1 , 0
       0     .12       0  221.73    .016       0  290.55     .12       0
   294.5    .045       0  309.85     .12       0  338.96     .06       0
   368.5     .12       0  398.04     .06       0  513.86     .12       0
#XS Ineff= 2 , 0
                          331.27         1131.49
Permanent Ineff=
       F       F
Bank Sta=294.5,309.85
XS Rating Curve= 0 ,0
Exp/Cntr=0.3,0.1

Type RM Length L Ch R = 1 ,5497.2  ,191.5,176.1,158.7
XS GIS Cut Line= 3
     1817118.783      271636.052     1817243.734      271444.149
     1817562.398      271436.407
#Sta/Elev= 30
       0 1194.76    28.6 1187.15    47.7 1181.55    85.9 1169.89    95.4 1167.37
     105 1165.28   171.8 1152.16   181.3 1150.07   190.8 1147.65   200.4 1144.54
  223.911135.954     229 1134.22   238.7 1132.31   248.3 1131.61     258    1130
   267.6 1126.19   274.7 1123.94   277.3 1123.11     287 1123.13   289.7 1123.69
   296.6 1125.13  304.271126.371  306.741126.735   315.9 1127.46  319.221127.535
   364.2 1127.84   383.6  1128.3  512.731133.665  543.591135.263   547.8 1135.51
#Mann= 9 ,-1 , 0
       0     .12       0  223.91    .016       0   274.7    .045       0
   289.7    .016       0  304.27     .12       0  306.74     .06       0
  319.22    .016       0  512.73     .06       0  543.59    .016       0
#XS Ineff= 2 , 0
                          313.93         1130.41
Permanent Ineff=
       F       F
Bank Sta=274.7,289.7
XS Rating Curve= 0 ,0
Exp/Cntr=0.3,0.1

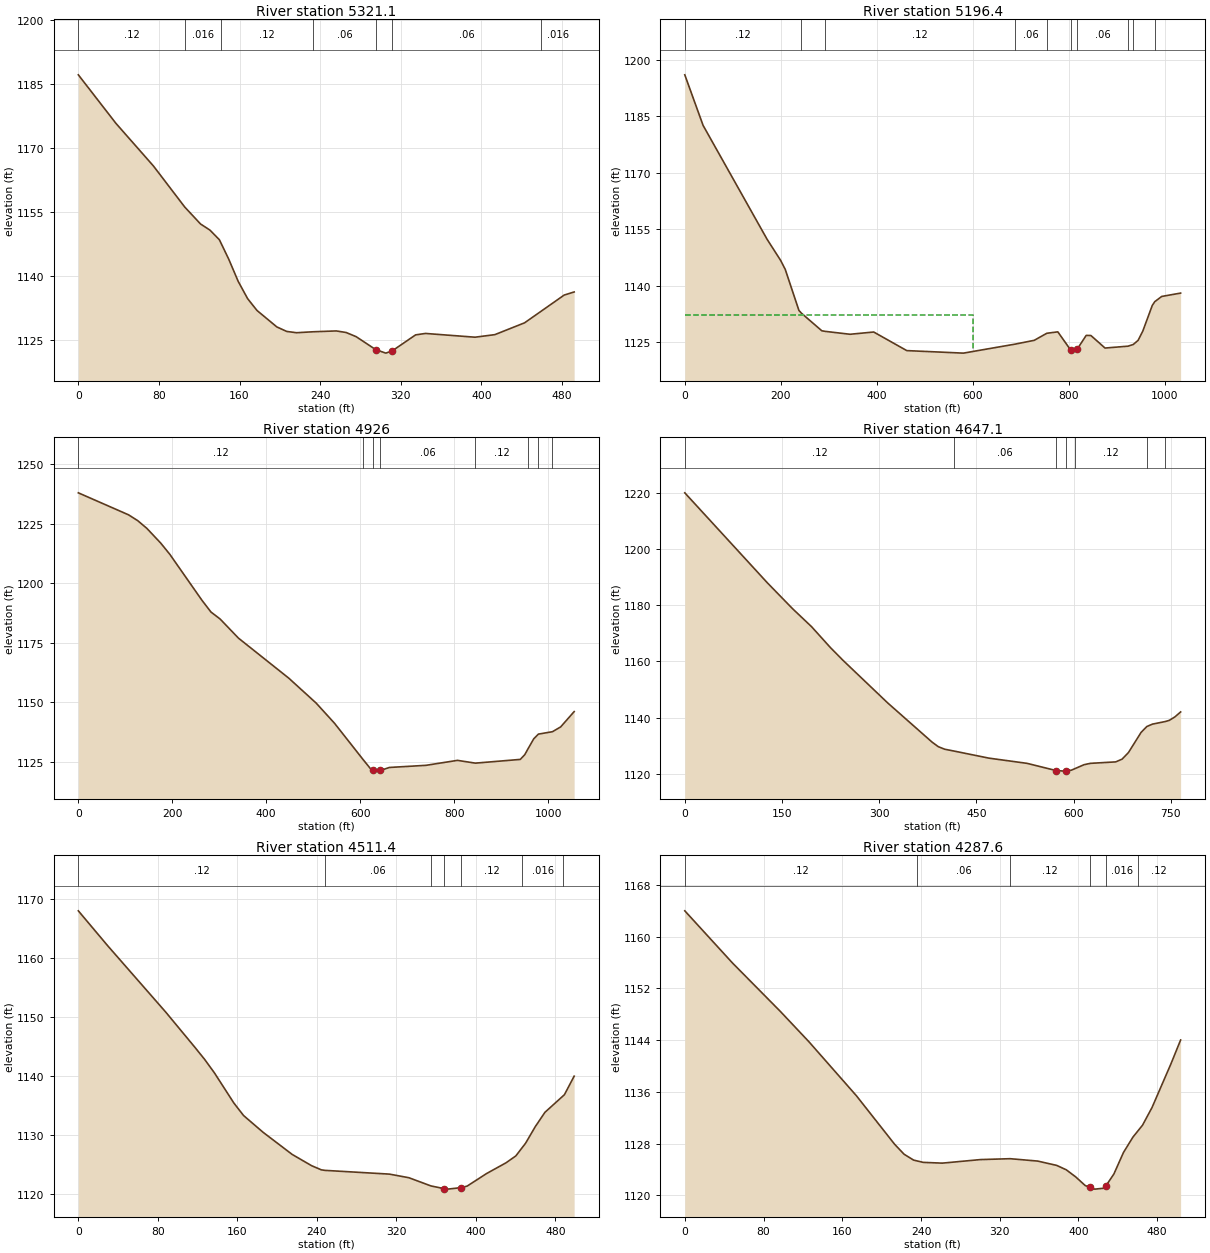
Type RM Length L Ch R = 1 ,5321.1  ,137.6,124.7,112
XS GIS Cut Line= 3
     1817153.795      271644.403     1817330.878      271635.723
      1817575.67      271437.806
#Sta/Elev= 30
       0 1187.07    37.3 1175.71    74.6  1165.7  105.661156.088   121.3 1152.13
   130.6  1150.7     140 1148.44  141.991147.464   149.3 1143.88   158.6 1138.72
     168 1134.65   177.3 1131.88     197 1128.02   206.8 1126.96   216.6 1126.66
   232.81126.879     256 1127.08   265.8 1126.71   275.7 1125.74   295.3 1122.68
   305.2 1121.88  311.791122.446   334.7 1126.15   344.5 1126.49   393.7 1125.61
   413.4 1126.21   442.9 1128.98  459.081131.653   482.2 1135.48   492.1 1136.21
#Mann= 7 ,-1 , 0
       0     .12       0  105.66    .016       0  141.99     .12       0
   232.8     .06       0   295.3    .045       0  311.79     .06       0
  459.08    .016       0
Bank Sta=295.3,311.79
XS Rating Curve= 0 ,0
Exp/Cntr=0.3,0.1

Type RM Length L Ch R = 1 ,5196.4  ,288.3,270.5,250
XS GIS Cut Line= 3
     1817111.075      272249.261     1817365.511      272119.774
     1817606.082      271411.764
#Sta/Elev= 30
       0    1196    38.1 1182.57   171.3 1152.35   199.8 1146.68   209.4 1144.29
   237.9 1133.39  242.871132.694   285.5    1128  292.771127.837   344.5 1127.07
   393.7 1127.67   462.6 1122.73   580.7 1122.06  688.291124.448   728.2 1125.46
  754.431127.335   777.4 1127.71  804.331122.857  818.331123.219   836.5 1126.77
   846.3 1126.74   875.8 1123.41  923.511123.905  934.66 1124.36   944.7 1125.46
   954.5 1127.92   974.2 1134.72  979.41 1135.73   993.9 1137.12  1033.3 1138.01
#Mann= 10 ,-1 , 0
       0     .12       0  242.87    .016       0  292.77     .12       0
  688.29     .06       0  754.43     .12       0  804.33    .045       0
  818.33     .06       0  923.51     .12       0  934.66     .06       0
  979.41    .016       0
#XS Ineff= 2 , 0
          600.62 1132.16
Permanent Ineff=
       F       F
Bank Sta=804.33,818.33
XS Rating Curve= 0 ,0
Exp/Cntr=0.3,0.1

Type RM Length L Ch R = 1 ,4926    ,278.8,278.9,277.8
XS GIS Cut Line= 3
     1818043.548      272311.829     1817624.124      271701.961
     1817669.214      271389.768
#Sta/Elev= 30
       0    1238   107.1 1228.73   126.6 1226.28   146.1 1223.01   175.3 1216.89
   194.8 1212.14     263 1192.87   282.4 1187.87   301.9 1184.93   340.9  1176.9
     448 1160.07   506.4 1149.57   545.4  1141.1  606.121125.872   623.3 1121.67
  627.881121.339     633 1120.97   642.8 1121.24   662.3 1122.51   740.2 1123.41
   807.1  1125.5  845.32 1124.33   940.9  1125.9   950.5  1127.9   956.91130.191
   969.6 1134.57  979.541136.539 1009.461137.549  1026.9 1139.57  1055.6    1146
#Mann= 8 ,-1 , 0
       0     .12       0  606.12     .06       0  627.88    .045       0
   642.8     .06       0  845.32     .12       0   956.9     .08       0
  979.54    .016       0 1009.46     .08       0
Bank Sta=627.88,642.8
XS Rating Curve= 0 ,0
Exp/Cntr=0.3,0.1

Type RM Length L Ch R = 1 ,4647.1  ,130.8,135.7,140.1
XS GIS Cut Line= 3
     1818086.879      272050.041      1817684.59      271472.133
     1817689.548      271411.366
#Sta/Elev= 30
       0    1220   127.1 1188.04   166.3 1178.75   195.6 1172.35   224.9 1164.86
   244.5 1160.29     313 1145.23   381.4 1131.29   391.2 1129.63     401 1128.73
  415.631128.066   469.4 1125.55   528.1  1123.7   573.11121.124   586.8 1120.93
   588.11120.976   596.6 1121.28  601.831121.798   616.1 1123.22   625.9  1123.7
     665 1124.22   674.8  1125.2   684.6 1127.54   704.1 1134.72   712.9  1136.8
   721.6 1137.66  741.371138.581   747.7 1139.01   756.4 1140.26   765.1    1142
#Mann= 7 ,-1 , 0
       0     .12       0  415.63     .06       0   573.1    .045       0
   588.1     .06       0  601.83     .12       0   712.9    .016       0
  741.37     .12       0
Bank Sta=573.1,588.1
XS Rating Curve= 0 ,0
Exp/Cntr=0.3,0.1

Type RM Length L Ch R = 1 ,4511.4  ,221.4,223.7,224.4
XS GIS Cut Line= 2
     1818030.193      271832.873     1817792.889      271394.046
#Sta/Elev= 30
       0    1168    29.4 1162.12      88 1150.85   117.4 1144.88   127.2 1142.83
     137 1140.56   156.5 1135.47   166.3 1133.35   185.9 1130.52   215.2 1126.77
   234.8 1124.86   244.6 1124.16  248.051124.075     313 1123.44   332.6 1122.83
  354.791121.443  367.611120.995   371.7  1120.9  385.54 1121.16   391.3 1121.42
   410.8 1123.54   430.4 1125.36   440.2 1126.52  446.491127.894     450 1128.66
   459.8 1131.48   469.5  1133.9  487.971136.708   489.1 1136.88   498.9 1140.02
#Mann= 7 ,-1 , 0
       0     .12       0  248.05     .06       0  354.79     .12       0
  367.61    .045       0  385.54     .12       0  446.49    .016       0
  487.97     .12       0
Bank Sta=367.61,385.54
XS Rating Curve= 0 ,0
Exp/Cntr=0.3,0.1

Type RM Length L Ch R = 1 ,4287.6  ,351.5,364.2,374.9
XS GIS Cut Line= 2
     1818179.337      271748.799     1817979.272      271286.403
#Sta/Elev= 30
       0    1164    48.4 1155.94    96.9 1148.47     126 1143.77   174.4 1135.39
   213.2 1127.89   222.8 1126.35   232.5 1125.44  235.961125.315   242.2 1125.09
   261.6 1124.97   300.4 1125.52  330.521125.657   358.5 1125.29   377.9 1124.62
   387.6 1123.94   397.2 1122.84   406.9  1121.5  411.951121.213   416.6 1120.95
   426.3  1121.1  427.621121.395     436 1123.29   445.7 1126.61   455.4 1129.01
  460.151129.906   465.1 1130.84   474.8 1133.59   494.1 1140.38   503.8 1144.02
#Mann= 6 ,-1 , 0
       0     .12       0  235.96     .06       0  330.52     .12       0
  411.95    .045       0  427.62    .016       0  460.15     .12       0
Bank Sta=411.95,427.62
XS Rating Curve= 0 ,0
Exp/Cntr=0.3,0.1

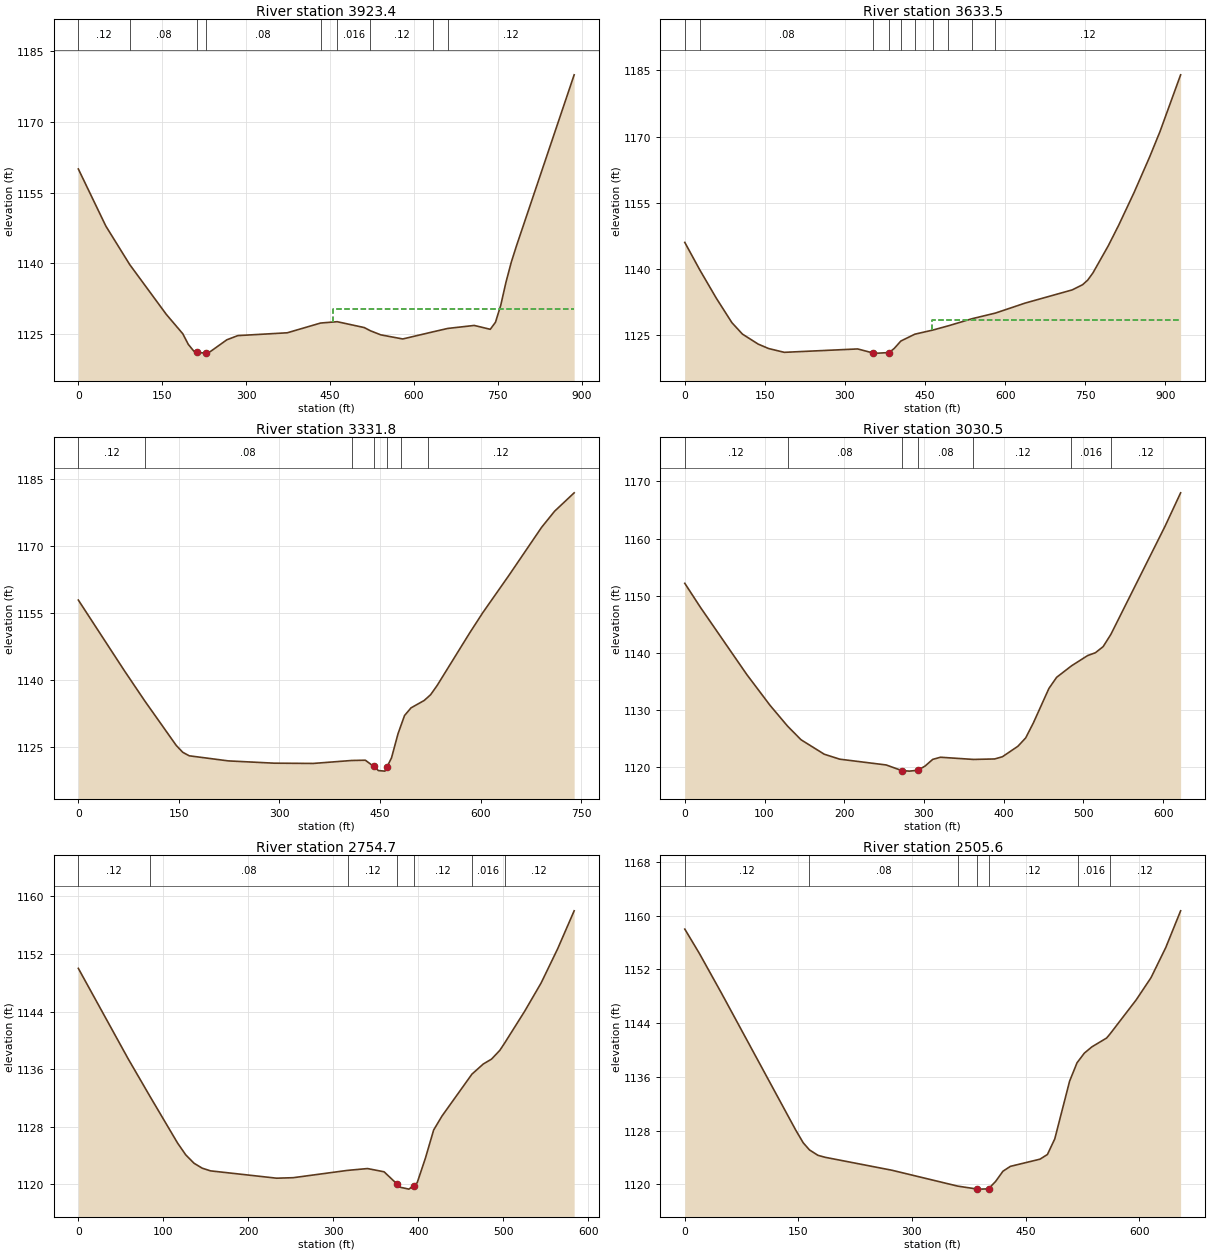
Type RM Length L Ch R = 1 ,3923.4  ,285.4,290,291.4
XS GIS Cut Line= 3
     1818286.294       271737.45       1818354.2       271022.95
     1818223.123      270916.601
#Sta/Elev= 30
       0    1160    49.2 1147.87   91.891139.689   157.3 1129.11   186.8 1124.99
   196.6 1122.74   206.5  1121.3   212.4 1121.07   226.1 1120.88   227.4 1120.92
     236 1121.21   265.5 1123.71   285.1  1124.6   373.6  1125.2  433.161127.273
  462.881127.556   511.2 1126.31  522.321125.625   540.8 1124.76   580.1 1123.89
  634.471125.414  660.551126.125   707.9 1126.76   736.5 1125.94   745.8 1127.43
   755.2 1131.02   764.6 1135.95     774 1140.16   783.4 1143.68   886.5    1180
#Mann= 9 ,-1 , 0
       0     .12       0   91.89     .08       0   212.4    .045       0
   227.4     .08       0  433.16     .06       0  462.88    .016       0
  522.32     .12       0  634.47     .06       0  660.55     .12       0
#XS Ineff= 2 , 0
                          455.11         1130.34
Permanent Ineff=
       F       F
Bank Sta=212.4,227.4
XS Rating Curve= 0 ,0
Exp/Cntr=0.3,0.1

Type RM Length L Ch R = 1 ,3633.5  ,291.7,301.7,311
XS GIS Cut Line= 3
     1818365.788      271699.936     1818511.388       271018.59
     1818713.812      270905.321
#Sta/Elev= 30
       0    1146   27.88 1139.81    58.9 1133.37    88.3 1127.79   107.9 1125.21
   137.4 1122.94     157 1121.93   186.4 1121.07   323.8 1121.84   353.3  1120.9
   363.1 1120.89   382.7 1121.02   392.5 1121.98  404.681123.632  430.77 1125.18
  465.311126.143  493.881127.092   538.3  1128.7  581.851129.973   637.8 1132.25
   725.7 1135.23     745  1136.4   754.7 1137.45   764.4 1139.07   793.4 1145.28
   812.7  1149.9   841.7 1157.36   870.7 1165.39     890 1171.12   928.7    1184
#Mann= 10 ,-1 , 0
       0     .12       0   27.88     .08       0   353.3    .045       0
   382.7     .12       0  404.68     .06       0  430.77    .016       0
  465.31     .06       0  493.88     .12       0   538.3     .06       0
  581.85     .12       0
#XS Ineff= 2 , 0
                          463.36         1128.51
Permanent Ineff=
       F       F
Bank Sta=353.3,382.7
XS Rating Curve= 0 ,0
Exp/Cntr=0.3,0.1

Type RM Length L Ch R = 1 ,3331.8  ,299,301.3,301.4
XS GIS Cut Line= 2
     1818462.342      271805.426      1818876.65      271192.871
#Sta/Elev= 30
       0    1158    68.1 1142.32   98.811135.482     146 1125.47   155.7 1123.93
   165.4 1123.14   223.8    1122   291.9 1121.49   350.3 1121.43  407.641122.093
   428.1 1122.15   440.61120.754   447.6 1119.83   457.3 1119.71  460.451120.664
   467.1 1122.68   476.8 1128.08  481.611130.098   486.5 1132.15   496.2 1133.87
   515.7 1135.51   522.21136.381   525.4 1136.81   535.2 1138.89   583.8 1150.67
   603.3 1155.19   642.2 1163.52   690.9 1174.27   710.3 1177.88   739.5    1182
#Mann= 7 ,-1 , 0
       0     .12       0   98.81     .08       0  407.64     .12       0
   440.6    .045       0  460.45     .12       0  481.61    .016       0
   522.2     .12       0
Bank Sta=440.6,460.45
XS Rating Curve= 0 ,0
Exp/Cntr=0.3,0.1

Type RM Length L Ch R = 1 ,3030.5  ,271.6,275.8,278.8
XS GIS Cut Line= 2
     1818593.778      271889.697       1819005.3      271423.413
#Sta/Elev= 30
       0 1152.16    19.4    1148    77.7 1136.21   106.9 1130.81  128.88 1127.17
   145.8 1124.78   174.9 1122.25   194.4 1121.38   252.6 1120.37   272.1 1119.39
   281.8 1119.29   292.1 1119.44   301.2 1120.16     311 1121.35   320.7 1121.72
  361.991121.337   388.7 1121.42   398.4 1121.81   417.8 1123.64   427.6 1125.11
   437.3 1127.76   456.7 1133.76   466.4 1135.71  485.011137.718   505.3 1139.52
     515 1140.01   524.7 1141.08  534.391143.218   602.5 1162.19   621.9    1168
#Mann= 7 ,-1 , 0
       0     .12       0  128.88     .08       0   272.1    .045       0
   292.1     .08       0  361.99     .12       0  485.01    .016       0
  534.39     .12       0
Bank Sta=272.1,292.1
XS Rating Curve= 0 ,0
Exp/Cntr=0.3,0.1

Type RM Length L Ch R = 1 ,2754.7  ,247.4,249.1,249.8
XS GIS Cut Line= 2
     1818729.152      271973.531     1819179.543      271602.891
#Sta/Elev= 30
       0    1150    58.3 1137.49   84.371132.182   116.7 1125.72   126.4 1124.06
   136.1  1122.9   145.8 1122.21   155.5 1121.84   233.3 1120.82   252.8 1120.89
  316.681121.906   340.2 1122.16   359.7 1121.71  375.331119.962   379.1 1119.55
   388.9  1119.3  394.371119.794   398.6 1120.18   408.3  1123.6     418 1127.52
   427.8 1129.46  463.051135.291   476.4  1136.7   486.1 1137.38   495.8 1138.59
  501.41 1139.59     525 1144.02   544.4 1147.96   563.8  1152.7   583.3    1158
#Mann= 7 ,-1 , 0
       0     .12       0   84.37     .08       0  316.68     .12       0
  375.33    .045       0  394.37     .12       0  463.05    .016       0
  501.41     .12       0
Bank Sta=375.33,394.37
XS Rating Curve= 0 ,0
Exp/Cntr=0.3,0.1

Type RM Length L Ch R = 1 ,2505.6  ,122.1,127.7,130.1
XS GIS Cut Line= 2
     1818827.591      272169.818     1819356.935      271784.427
#Sta/Elev= 30
       0    1158    19.6 1154.31    48.9 1148.37   146.6 1128.06   156.4 1126.19
  164.671125.124   175.9 1124.32   185.7 1124.02   273.6  1122.1  360.331119.741
   386.1  1119.3   390.9 1119.29   401.1 1119.34   410.5 1120.44   420.2 1121.96
     430 1122.68   469.1 1123.75   478.9 1124.45   488.6 1126.77   508.2 1135.37
     518  1138.1  519.55 1138.33   527.7 1139.54   537.5 1140.46     557 1141.78
  561.381142.361   596.1 1147.46   615.7 1150.77   635.2 1155.26   654.8 1160.72
#Mann= 7 ,-1 , 0
       0     .12       0  164.67     .08       0  360.33     .12       0
   386.1    .045       0   401.1     .12       0  519.55    .016       0
  561.38     .12       0
Bank Sta=386.1,401.1
XS Rating Curve= 0 ,0
Exp/Cntr=0.3,0.1

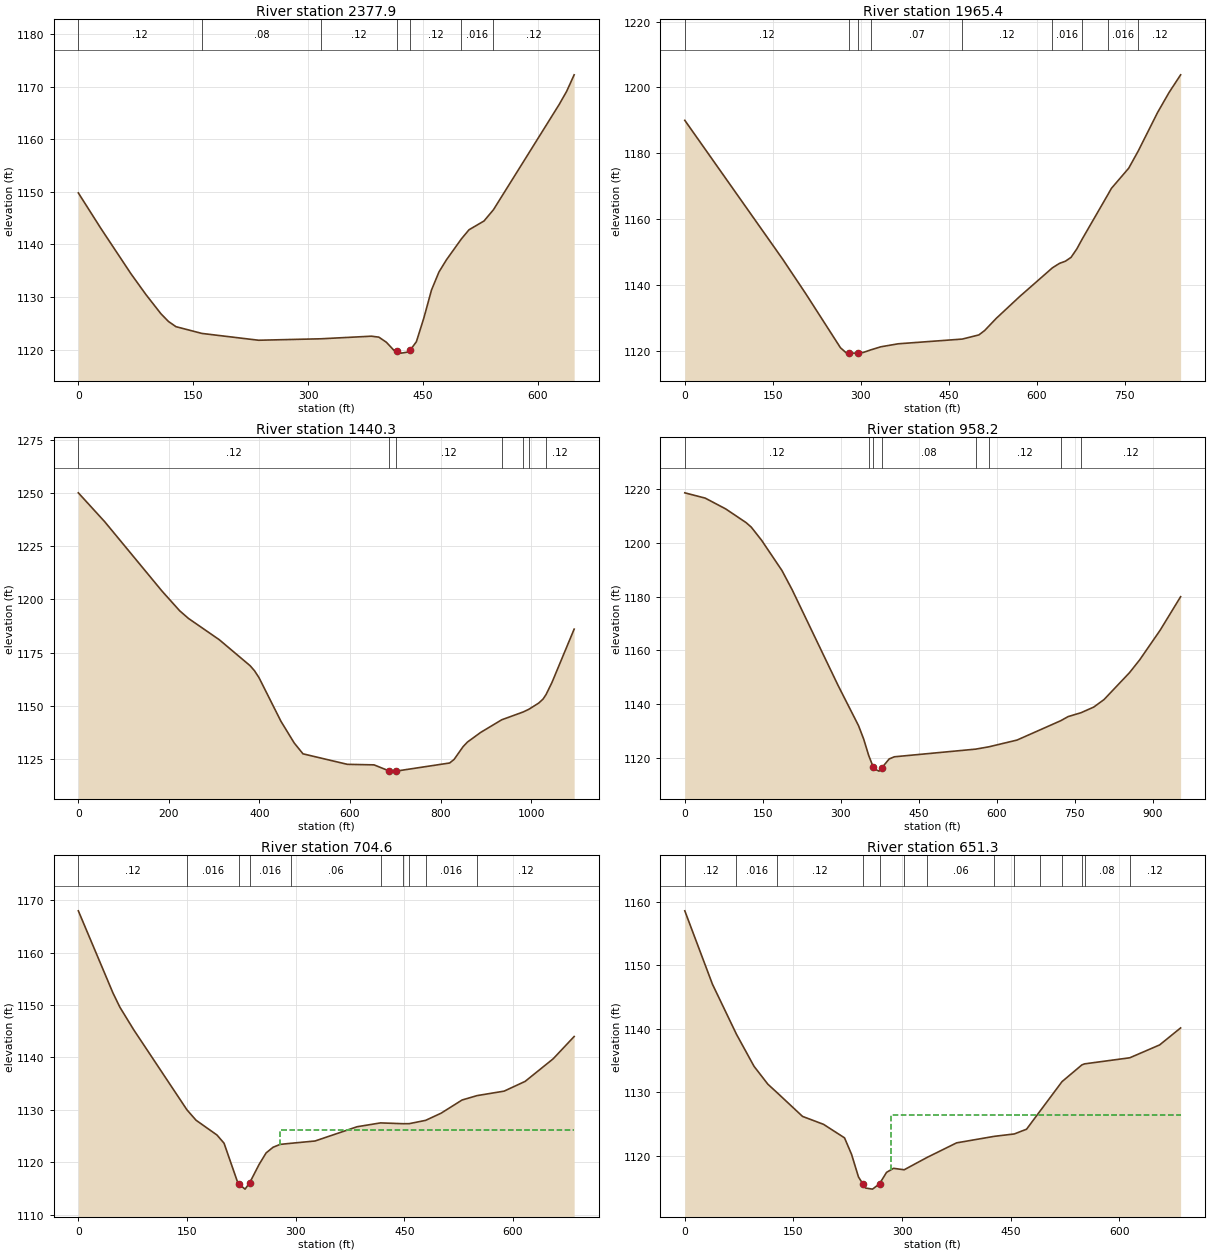
Type RM Length L Ch R = 1 ,2377.9  ,421.3,412.5,403
XS GIS Cut Line= 2
     1818892.435      272210.052     1819436.405      271858.937
#Sta/Elev= 30
       0  1149.8    29.4 1143.06    68.7 1134.43    88.3 1130.46   107.9 1126.81
   117.7 1125.35   127.5 1124.36   161.41123.074   235.4 1121.78  316.741122.057
   382.6 1122.55   392.4 1122.37   402.2  1121.4     412 1119.88  415.53 1119.68
   421.8 1119.33   431.6 1119.57   433.11119.863   441.4  1121.5   451.2 1126.04
   461.1 1131.32   470.9 1134.77   480.7 1137.09  500.25 1141.07   510.1 1142.79
   529.7 1144.46  542.061146.611   627.8 1166.61   637.6 1169.12   647.4 1172.26
#Mann= 7 ,-1 , 0
       0     .12       0   161.4     .08       0  316.74     .12       0
  415.53    .045       0   433.1     .12       0  500.25    .016       0
  542.06     .12       0
Bank Sta=415.53,433.1
XS Rating Curve= 0 ,0
Exp/Cntr=0.3,0.1

Type RM Length L Ch R = 1 ,1965.4  ,529.1,525.1,514.1
XS GIS Cut Line= 2
     1819095.556      272611.064     1819575.163      271914.637
#Sta/Elev= 30
       0    1190   167.2 1147.76   206.5 1137.28   265.5 1120.92   275.3 1119.38
   279.6 1119.34   285.1 1119.29   294.6 1119.29   304.8 1119.52  316.871120.259
   334.3 1121.21   363.8 1122.12  473.231123.559   501.5 1124.82   511.3 1126.14
     531 1129.82   570.3 1136.35   626.91145.194   639.1 1146.56     649  1147.2
   658.8 1148.39   668.6 1150.95  677.691153.918  721.951167.558   727.6 1169.34
   757.1 1175.47  773.481180.743   806.3 1192.38   825.9 1198.46   845.6 1203.82
#Mann= 9 ,-1 , 0
       0     .12       0   279.6    .045       0   294.6     .12       0
  316.87     .07       0  473.23     .12       0   626.9    .016       0
  677.69     .12       0  721.95    .016       0  773.48     .12       0
Bank Sta=279.6,294.6
XS Rating Curve= 0 ,0
Exp/Cntr=0.3,0.1

Type RM Length L Ch R = 1 ,1440.3  ,481.6,482.1,480.2
XS GIS Cut Line= 3
     1819207.603      272892.719      1819655.11      272617.577
     1819693.579      272049.278
#Sta/Elev= 30
       0    1250    58.4  1236.4   184.8 1203.86   223.8 1194.61   243.2 1191.02
   311.3 1181.02   379.4 1168.81   389.1 1166.44   398.9 1163.24   447.5 1142.69
   476.7 1132.55   496.1 1127.44   594.1 1122.51     653 1122.26  686.241119.413
   692.3 1119.32   702.1 1119.34   819.9 1123.14   829.8 1124.82   849.4 1130.75
   859.2 1132.96   888.7 1137.53  934.87 1143.42  982.421147.105  994.811148.361
  1016.4 1151.24  1026.2 1153.15 1032.931155.313  1045.8 1160.91  1094.9    1186
#Mann= 7 ,-1 , 0
       0     .12       0  686.24    .045       0   702.1     .12       0
  934.87    .016       0  982.42     .12       0  994.81    .016       0
 1032.93     .12       0
Bank Sta=686.24,702.1
XS Rating Curve= 0 ,0
Exp/Cntr=0.3,0.1

Type RM Length L Ch R = 1 ,958.2   ,260.8,253.7,246.1
XS GIS Cut Line= 2
     1819943.933      273020.806     1819924.609      272066.905
#Sta/Elev= 30
       0 1218.69    39.3 1216.72    78.7  1212.7     118 1207.59   127.9 1205.91
   147.5 1201.09   186.9 1189.77   206.6 1182.58   295.1 1146.89   334.4 1131.92
   344.3 1126.92  353.941120.821   362.3  1116.7   363.9 1115.92   373.8 1115.02
   378.91116.198   393.4 1119.57   403.3 1120.36  559.761123.215     5851124.069
   639.3 1126.59  723.09 1133.77   737.7 1135.34  762.621136.788   786.9 1138.88
   806.6 1141.66   855.7 1151.69   875.4 1156.49   914.8 1167.54   954.1    1180
#Mann= 8 ,-1 , 0
       0     .12       0  353.94     .08       0   362.3    .045       0
   378.9     .08       0  559.76     .06       0     585     .12       0
  723.09    .016       0  762.62     .12       0
Bank Sta=362.3,378.9
XS Rating Curve= 0 ,0
Exp/Cntr=0.3,0.1

Type RM Length L Ch R = 1 ,704.6   ,52.7,53.3,54.3
XS GIS Cut Line= 3
     1820152.541      272849.655     1820211.415      272698.198
     1820038.068      272205.799
#Sta/Elev= 30
       0    1168    47.8 1152.32    57.4 1149.59    76.5 1145.28   150.11129.973
   162.5 1128.02   191.5 1125.18   201.2 1123.62   220.5 1115.94   221.5 1115.83
   230.2 1114.86   236.5 1116.06   249.5 1119.56   259.2 1121.77   268.8 1122.85
   278.5  1123.4  294.04 1123.62   326.8 1124.05   384.8 1126.77  417.221127.507
  448.351127.351  456.831127.361  479.491127.993   500.8 1129.36   529.8 1131.88
  550.451132.716   587.8 1133.57   616.8 1135.43   655.5 1139.74   684.5    1144
#Mann= 10 ,-1 , 0
       0     .12       0   150.1    .016       0   221.5    .045       0
   236.5    .016       0  294.04     .06       0  417.22     .08       0
  448.35    .016       0  456.83     .06       0  479.49    .016       0
  550.45     .12       0
#XS Ineff= 2 , 0
                          278.12         1126.22
Permanent Ineff=
       F       F
Bank Sta=221.5,236.5
XS Rating Curve= 0 ,0
Exp/Cntr=0.3,0.1

Type RM Length L Ch R = 1 ,651.3   ,128,140.1,151.8
XS GIS Cut Line= 3
     1820211.135      272858.336     1820270.008      272706.879
     1820096.661      272214.479
#Sta/Elev= 30
       0 1158.56    38.2 1146.99    71.31139.117    95.6 1134.06   114.7 1131.24
  127.361129.918   162.5 1126.17   191.5 1124.92   220.5 1122.79   230.2  1120.2
   239.8 1116.62   246.4 1115.44   249.5 1114.88   259.2 1114.71   268.8 1115.55
   278.5 1117.35   288.2 1117.99  302.851117.758  333.991119.676   375.2    1122
  427.39 1123.03  454.841123.402   471.8 1124.15  490.411127.001   520.81131.653
   548.21134.284  551.931134.447  614.311135.405   655.5 1137.43   684.5 1140.11
#Mann= 14 ,-1 , 0
       0     .12       0    71.3    .016       0  127.36     .12       0
   246.4    .045       0   268.8     .12       0  302.85     .08       0
  333.99     .06       0  427.39     .08       0  454.84    .016       0
  490.41     .06       0   520.8     .08       0   548.2     .06       0
  551.93     .08       0  614.31     .12       0
#XS Ineff= 2 , 0
                          284.62         1126.39
Permanent Ineff=
       F       F
Bank Sta=246.4,268.8
XS Rating Curve= 0 ,0
Exp/Cntr=0.3,0.1

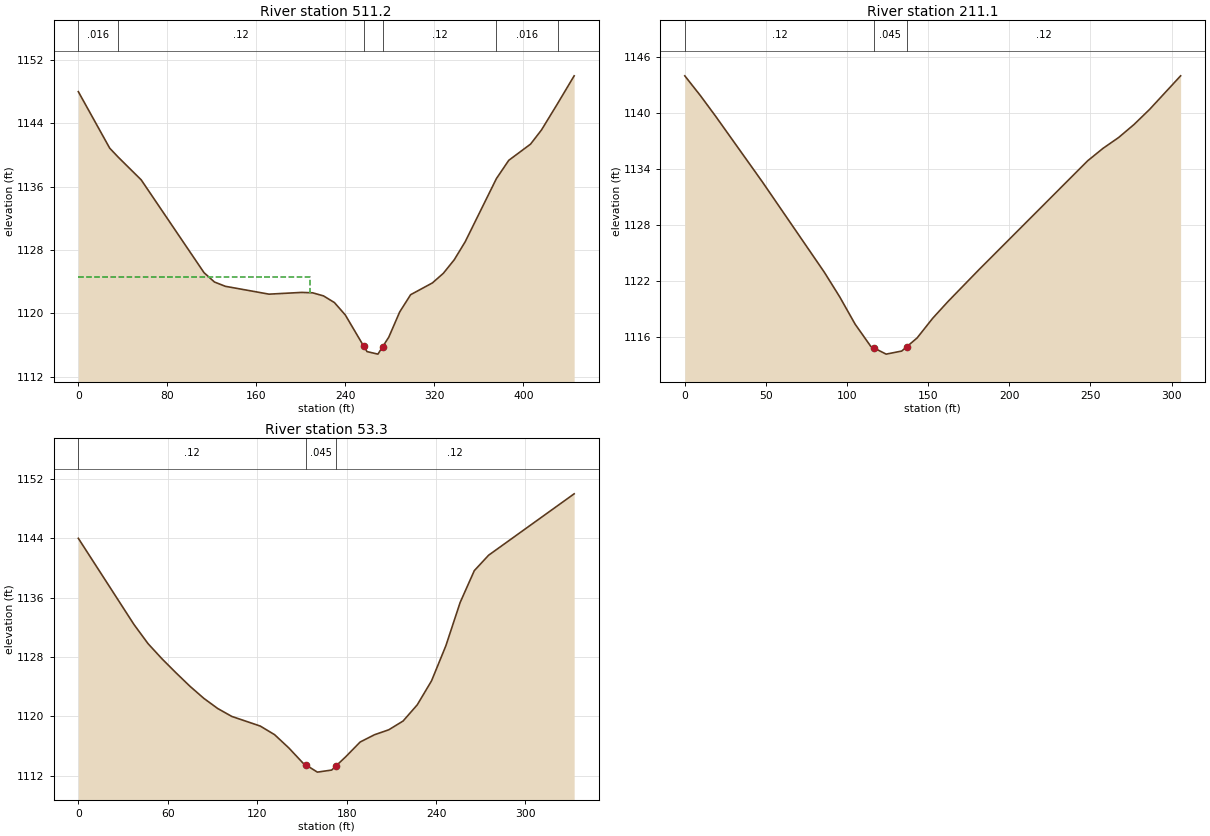
Type RM Length L Ch R = 1 ,511.2   ,275,300.1,325.2
XS GIS Cut Line= 3
     1820269.469      272884.002     1820339.981      272783.962
     1820409.609      272468.271
#Sta/Elev= 30
       0    1148    28.2 1140.87   35.921139.724    56.5 1136.87     113 1125.15
   122.4 1123.97   132.2 1123.43   171.4 1122.44   200.8 1122.66   210.6 1122.61
   220.4 1122.22   230.2 1121.38     240 1119.81  256.391115.907   259.5 1115.19
   269.3 1114.87   273.6 1115.81   279.1 1117.02   288.9  1120.2   298.7 1122.37
   318.3 1123.86   328.1 1125.07   337.9 1126.78   347.7 1129.04  375.841137.034
   386.9 1139.33   406.5 1141.38   416.3 1143.16  430.761146.484   445.7    1150
#Mann= 6 ,-1 , 0
       0    .016       0   35.92     .12       0  256.39    .045       0
   273.6     .12       0  375.84    .016       0  430.76     .12       0
#XS Ineff= 2 , 0
          207.95 1124.66
Permanent Ineff=
       F       F
Bank Sta=256.39,273.6
XS Rating Curve= 0 ,0
Exp/Cntr=0.3,0.1

Type RM Length L Ch R = 1 ,211.1   ,161.5,157.8,154.4
XS GIS Cut Line= 2
     1820333.343      272941.267     1820627.462       272858.34
#Sta/Elev= 22
       0    1144     9.6 1141.88    19.1 1139.64    47.8 1132.62      86 1122.92
    95.5 1120.27     105 1117.34   114.6 1114.97   116.7 1114.78   124.1 1114.13
   133.7 1114.46  136.73 1114.91   143.2 1115.87   152.8 1117.98   162.3 1119.79
   181.4 1123.21   248.3 1134.88   257.8 1136.22   267.4 1137.38   276.9 1138.78
   286.5  1140.4   305.6    1144
#Mann= 3 ,-1 , 0
       0     .12       0   116.7    .045       0  136.73     .12       0
Bank Sta=116.7,136.73
XS Rating Curve= 0 ,0
Exp/Cntr=0.3,0.1

Type RM Length L Ch R = 1 ,53.3    ,56.7,53.3,49.3
XS GIS Cut Line= 3
     1820366.123      273066.191      1820468.82      273073.714
     1820677.256      272977.032
#Sta/Elev= 29
       0    1144    37.4 1132.36    46.8 1129.79    56.2 1127.74    65.5 1125.87
    74.9 1124.05    84.2 1122.42    93.6 1121.04     103 1119.98   122.1 1118.68
   131.7 1117.52   141.3 1115.72   150.8 1113.68   152.7 1113.44   160.4 1112.47
     170 1112.75  173.171113.354   179.6 1114.58   189.1 1116.53   198.7 1117.51
   208.3 1118.18   217.9 1119.36   227.4 1121.54     237 1124.78   246.6  1129.5
   256.2 1135.35   265.7 1139.64   275.3 1141.72   332.7    1150
#Mann= 3 ,-1 , 0
       0     .12       0   152.7    .045       0  173.17     .12       0
Bank Sta=152.7,173.17
XS Rating Curve= 0 ,0
Exp/Cntr=0.3,0.1

Chan Stop Cuts=-1
Use User Specified Reach Order=0
Composite Channel Slope=5